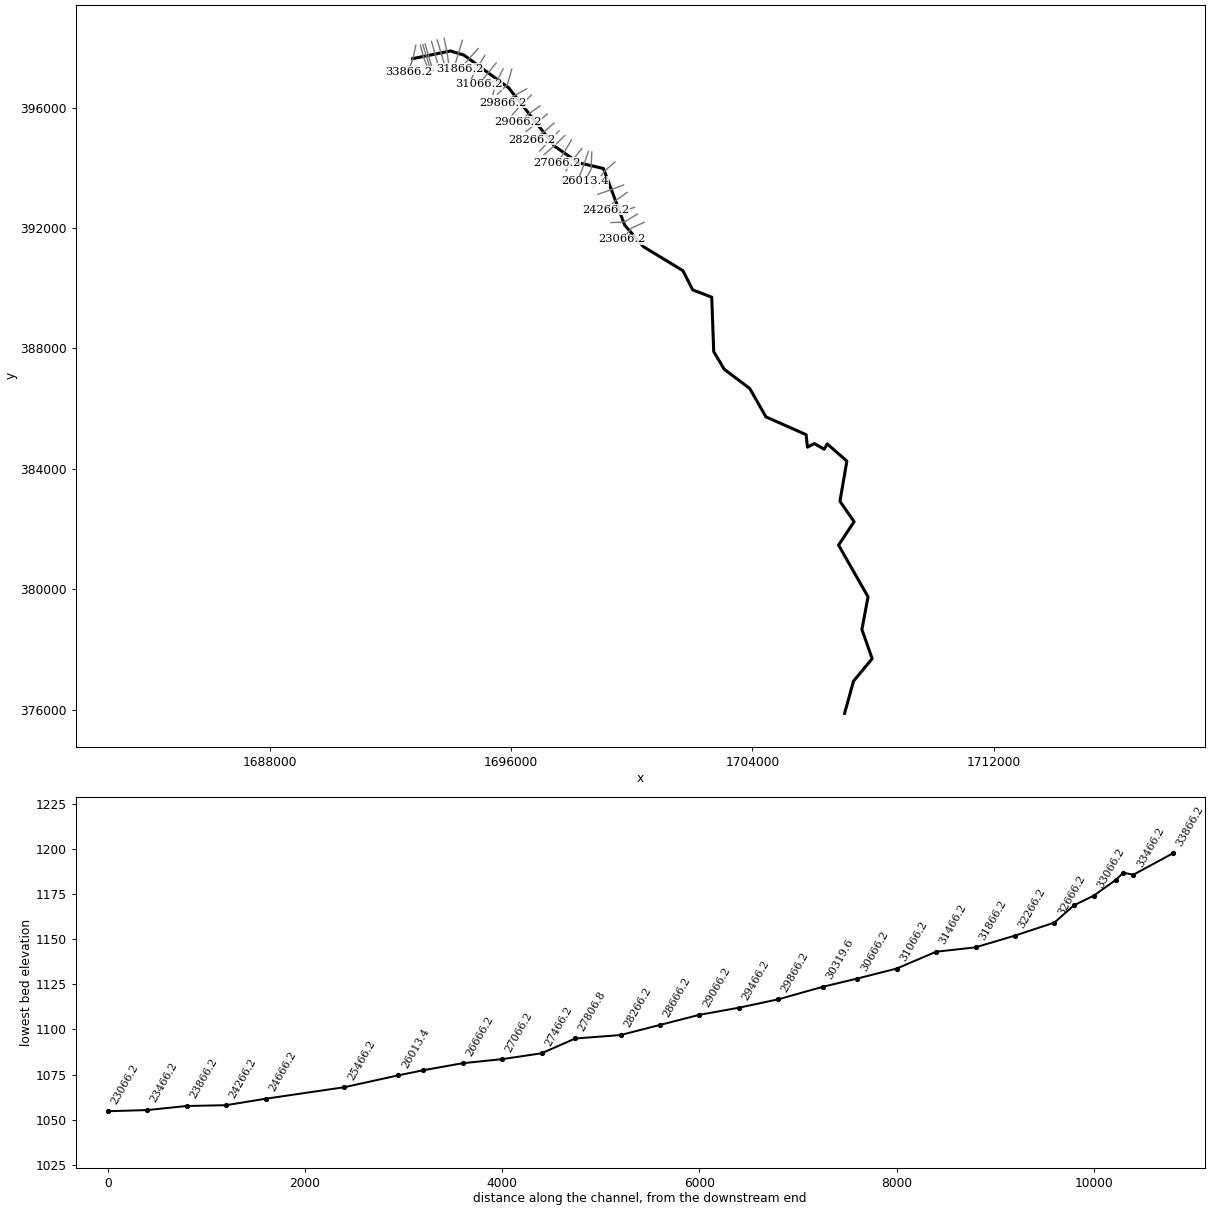
--- BrthlmwFrk.prj (project) ---

Proj Title=BrthlmwFrk
Current Plan=p01
Geom File=g01
Flow File=f01
Plan File=p01
DSS Export Rating Curves=0
DSS Export Rating Curve Sorted=0
DSS Export Volume Flow Curves=0
DXF OffsetX=0
DXF OffsetY=0
DXF ScaleX=0
DXF ScaleY=0

--- BrthlmwFrk.p01 (plan) ---

Plan Title=Floodplain
Program Version=4.00
Geom File=g01
Flow File=f01
K Sum by GR=0
Std Step Tol=0.01
Critical Tol=0.01
Num of Std Step Trials=20
Max Error Tol=0.3
Flow Tol Ratio=0.001
Split Flow NTrial=30
Split Flow Tol=0.02
Split Flow Ratio=0.02
Log Output Level=0
Friction Slope Method=1
Unsteady Friction Slope Method=2
Unsteady Bridges Friction Slope Method=1
Global Log Level=0
CheckData=False
Run HTab=0
Run UNet=0
Run PostProcess=0
UNET Theta=0
UNET Theta Warmup=0
UNET ZTol=0
UNET ZSATol=0
UNET MxIter=0
UNET MaxInSteps=0
UNET DtIC=0
UNET DtMin=0
UNET MaxCRTS=0
UNET WFStab=0
UNET SFStab=0
UNET WFX=0
UNET SFX=0
UNET DSS MLevel=0
UNET DZMax Abort=0
UNET Convert EG Bridges=0
UNET Use Existing IB Tables=0
UNET Froude Limit=0
UNET Froude Power=0
Write IC File=0
Echo Input=False
Echo Output=False
Write Detailed=0

--- BrthlmwFrk.f01 (steady flow) ---

Flow Title=NFF Regression Equation
Program Version=4.00
Number of Profiles=1
Profile Names=P100yr
River Rch & RM=BrthlmwFrk,Main      ,33866.2
     136
River Rch & RM=BrthlmwFrk,Main      ,33466.2
     136
River Rch & RM=BrthlmwFrk,Main      ,33364.8
     161
River Rch & RM=BrthlmwFrk,Main      ,33066.2
     184
River Rch & RM=BrthlmwFrk,Main      ,32666.2
     205
River Rch & RM=BrthlmwFrk,Main      ,32266.2
     400
River Rch & RM=BrthlmwFrk,Main      ,31866.2
     406
River Rch & RM=BrthlmwFrk,Main      ,31866.2
     461
River Rch & RM=BrthlmwFrk,Main      ,30666.2
     490
River Rch & RM=BrthlmwFrk,Main      ,29866.2
     538
River Rch & RM=BrthlmwFrk,Main      ,29466.2
     564
River Rch & RM=BrthlmwFrk,Main      ,27466.2
     623
River Rch & RM=BrthlmwFrk,Main      ,25466.2
     669
River Rch & RM=BrthlmwFrk,Main      ,25466.2
    1125
River Rch & RM=BrthlmwFrk,Main      ,23066.2
    1214
River Rch & RM=BrthlmwFrk,Main      ,18266.2
    1328
River Rch & RM=BrthlmwFrk,Main      ,17866.2
    1979
River Rch & RM=BrthlmwFrk,Main      ,14590.9
    2083
River Rch & RM=BrthlmwFrk,Main      ,9866.2
    2292
River Rch & RM=BrthlmwFrk,Main      ,266.2
    2545
Boundary for River Rch & Prof#=BrthlmwFrk,Main      ,1
Up Type=0
Dn Type=3
Dn Slope=0.00208

--- BrthlmwFrk.g01 (geometry) ---

Geom Title=USGS 3m DEM
Program Version=4.00

River Reach=BrthlmwFrk     ,Main
Reach XY= 30
     1692738.555      397627.659     1693997.307      397883.698
     1694443.740      397743.850     1695927.065      396655.861
     1697445.474      394719.715     1698232.234      394171.258
     1699064.359      393979.382     1699768.756      392098.709
     1700383.540      391385.809     1701698.339      390584.386
     1702022.085      389947.933     1702654.516      389702.955
     1702719.790      387897.541     1703067.686      387309.088
     1703914.214      386670.301     1704451.403      385726.763
     1705783.311      385135.072     1705827.117      384718.960
     1706055.182      384840.493     1706381.571      384651.786
     1706483.182      384827.880     1707133.464      384257.792
     1706904.115      382922.510     1707373.789      382244.198
     1706858.490      381466.381     1707835.098      379748.745
     1707632.175      378660.797     1707971.512      377694.464
     1707354.031      376946.632     1707057.236      375875.777

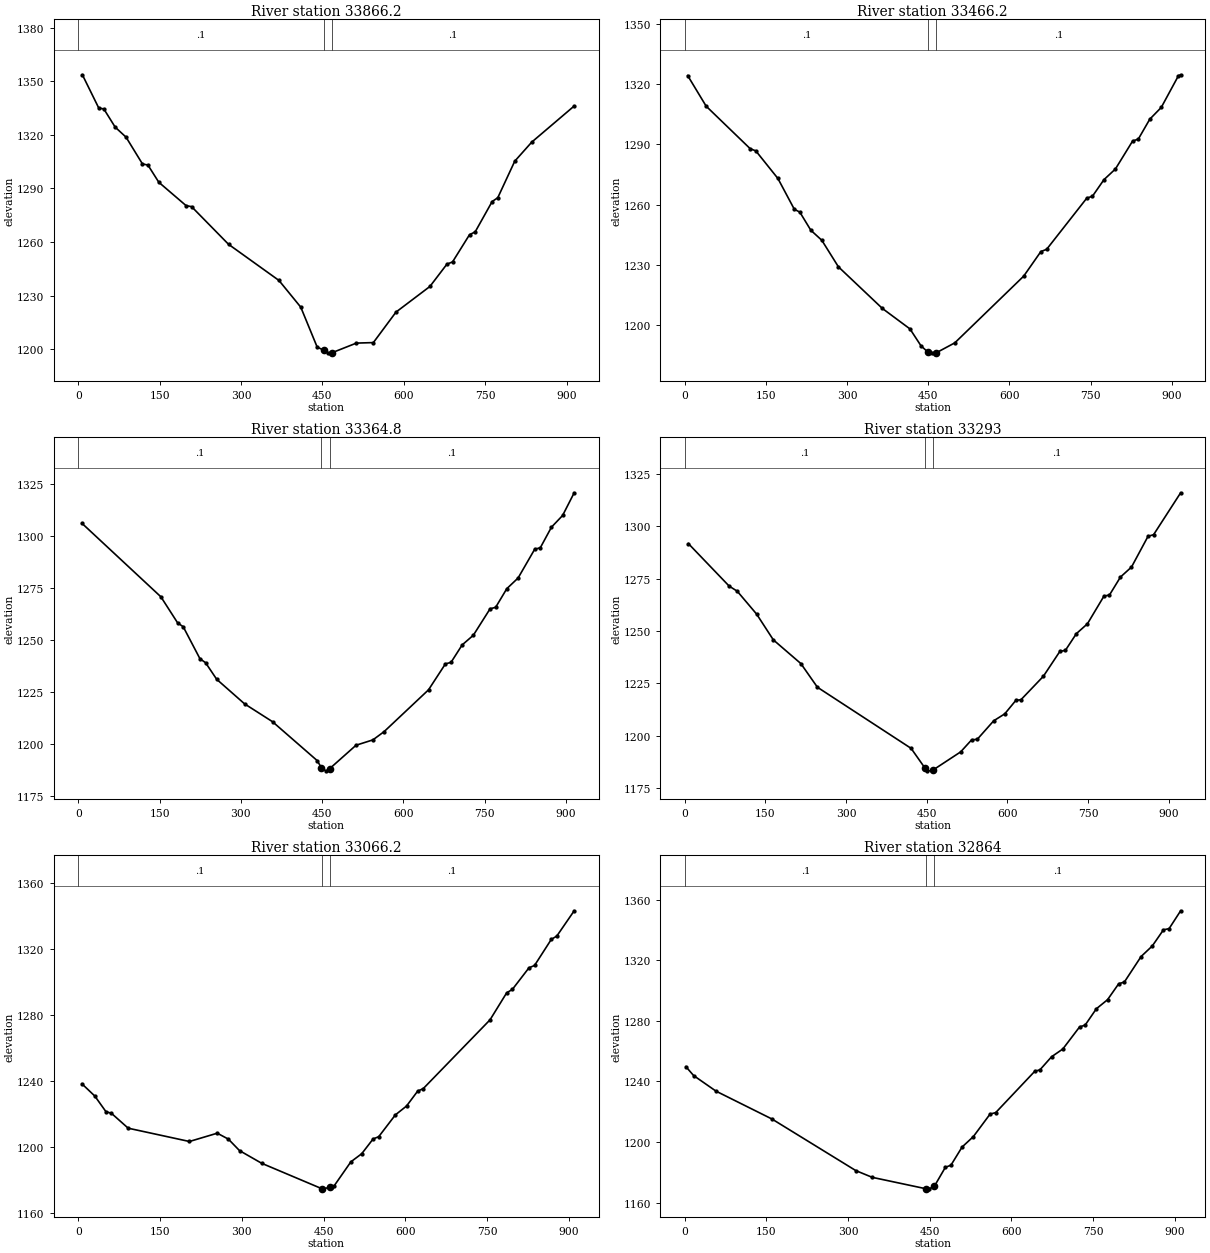
Type RM Length L Ch R = 1 ,33866.2,380.8,400,418.9
XS GIS Cut Line= 3
     1692845.028      398073.956     1692747.971      397624.291
     1692597.700      397195.769
#Sta/Elev= 30
     7.5 1353.68    37.7 1335.05    47.0 1334.57    67.9 1324.38    88.0 1318.74
   118.2 1303.76   128.3 1303.12   148.4 1293.47   198.7 1280.38   208.8 1279.82
   276.9 1258.73   369.9 1238.47   410.1 1223.49   440.3 1201.15   452.5 1199.36
   460.9 1197.75   467.5 1197.95   512.6 1203.37   543.9 1203.65   585.6 1220.73
   648.2 1235.11   679.5 1247.59   689.9 1248.86   721.2 1264.11   731.6 1265.68
   762.9 1282.67   773.3 1284.83   804.6 1305.30   835.9 1315.97   914.1 1336.19
#Mann= 3 , 0 , 0
       0     0.1       0   452.5   0.045       0   467.5     0.1       0
Bank Sta=   452.5,   467.5
Exp/Cntr=0.3,0.1

Type RM Length L Ch R = 1 ,33466.2,100.5,101.4,99.6
XS GIS Cut Line= 3
     1692998.102      398075.347     1693115.414      397633.056
     1693285.589      397206.851
#Sta/Elev= 30
     5.3 1324.37    39.5 1309.09   121.0 1287.85   131.2 1286.82   172.1 1273.03
   202.4 1257.68   212.6 1256.24   233.0 1247.19   253.3 1242.18   283.9 1228.96
   365.2 1208.18   416.2 1197.97   436.6 1189.54   450.1 1186.22   456.9 1185.89
   465.1 1186.10   499.1 1191.02   626.4 1224.29   658.2 1236.57   668.8 1237.67
   743.0 1263.20   753.6 1264.20   774.8 1272.44   796.0 1277.77   827.7 1291.68
   838.3 1292.69   859.5 1302.61   880.7 1308.47   912.5 1324.31   916.5 1324.74
#Mann= 3 , 0 , 0
       0     0.1       0   450.1   0.045       0   465.1     0.1       0
Bank Sta=   450.1,   465.1
Exp/Cntr=0.3,0.1

Type RM Length L Ch R = 1 ,33364.8,72.1,71.8,71.4
XS GIS Cut Line= 2
     1693078.317      398094.171     1693348.353      397219.768
#Sta/Elev= 30
     6.6 1306.21   152.4 1270.86   183.3 1258.33   193.6 1256.48   224.5 1241.10
   234.8 1239.21   255.4 1231.22   306.9 1219.41   358.4 1210.85   440.8 1192.17
   448.8 1188.67   457.6 1187.09   463.8 1188.25   512.6 1199.54   543.7 1202.10
   564.3 1206.05   646.4 1226.17   677.6 1238.65   687.9 1239.35   708.5 1247.75
   729.1 1252.39   760.0 1265.10   770.3 1265.82   790.9 1274.78   811.7 1279.90
   842.4 1293.75   852.7 1294.43   873.3 1304.33   893.9 1309.96   915.2 1320.84
#Mann= 3 , 0 , 0
       0     0.1       0   448.8   0.045       0   463.8     0.1       0
Bank Sta=   448.8,   463.8
Exp/Cntr=0.3,0.1

Type RM Length L Ch R = 1 ,33293,227.1,226.8,226.5
XS GIS Cut Line= 2
     1693152.818      398116.433     1693411.764      397231.100
#Sta/Elev= 30
     6.7 1291.62    82.6 1271.36    97.5 1268.96   133.6 1258.04   164.7 1245.76
   215.9 1234.47   246.7 1223.19   421.0 1194.07   446.3 1184.86   450.9 1183.22
   461.3 1183.67   513.2 1192.39   533.7 1198.15   544.0 1198.36   574.7 1207.21
   595.2 1210.50   615.8 1216.91   625.4 1217.25   667.0 1228.39   697.8 1240.28
   708.0 1240.75   728.5 1248.73   749.0 1253.41   779.8 1266.62   790.0 1267.12
   810.5 1275.70   831.0 1280.45   861.8 1295.12   872.1 1295.87   922.4 1315.82
#Mann= 3 , 0 , 0
       0     0.1       0   446.3   0.045       0   461.3     0.1       0
Bank Sta=   446.3,   461.3
Exp/Cntr=0.3,0.1

Type RM Length L Ch R = 1 ,33066.2,201.8,202.2,202.6
XS GIS Cut Line= 3
     1693365.386      398203.963     1693487.828      397765.748
     1693610.270      397327.532
#Sta/Elev= 30
     6.6 1238.15    30.2 1230.77    50.6 1221.31    60.8 1220.28    91.5 1211.27
   203.9 1203.21   255.0 1208.24   275.4 1204.64   295.8 1197.69   336.7 1189.97
   447.5 1174.52   449.1 1174.34   462.5 1175.70   469.5 1176.33   500.2 1190.88
   520.1 1195.80   541.0 1204.74   551.3 1206.12   581.9 1219.34   602.3 1224.68
   622.8 1233.74   633.0 1235.25   755.6 1276.94   786.2 1293.33   796.5 1295.34
   827.1 1308.48   837.3 1309.89   868.0 1325.67   878.2 1327.73   910.0 1343.00
#Mann= 3 , 0 , 0
       0     0.1       0   447.5   0.045       0   462.5     0.1       0
Bank Sta=   447.5,   462.5
Exp/Cntr=0.3,0.1

Type RM Length L Ch R = 1 ,32864,199.8,197.8,194.6
XS GIS Cut Line= 2
     1693553.533      398249.523     1693815.372      397377.209
#Sta/Elev= 30
     2.0 1249.75    16.3 1243.85    57.4 1233.58   160.1 1215.20   314.2 1181.14
   344.3 1176.70   443.4 1169.13   447.8 1168.92   458.4 1170.79   478.6 1183.30
   488.9 1184.73   509.4 1196.72   530.0 1203.57   560.8 1218.46   571.1 1219.42
   643.0 1246.75   652.3 1247.63   673.8 1256.31   694.4 1261.40   725.2 1275.98
   735.4 1277.18   756.0 1287.96   776.5 1293.93   797.1 1304.50   807.4 1305.58
   838.2 1322.45   858.7 1329.40   879.3 1340.09   889.6 1340.85   910.8 1352.61
#Mann= 3 , 0 , 0
       0     0.1       0   443.4   0.045       0   458.4     0.1       0
Bank Sta=   443.4,   458.4
Exp/Cntr=0.3,0.1

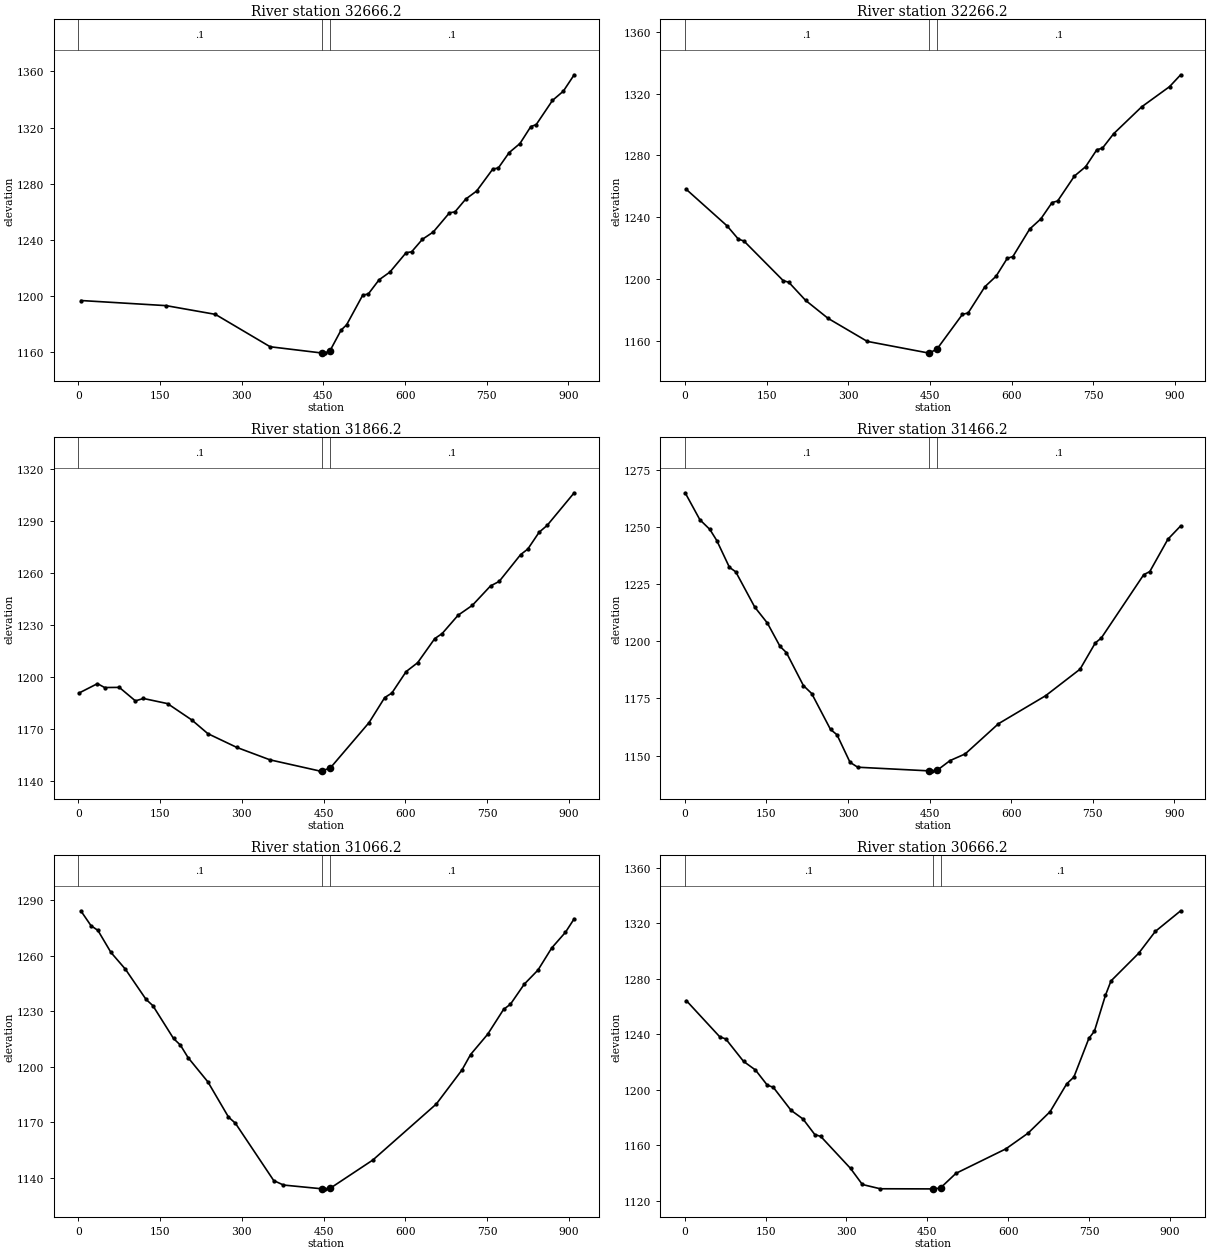
Type RM Length L Ch R = 1 ,32666.2,411.4,400,390
XS GIS Cut Line= 3
     1693783.965      398303.132     1693876.845      397857.876
     1693944.259      397406.981
#Sta/Elev= 30
     5.0 1196.81   161.2 1193.17   251.6 1186.96   352.2 1163.88   447.3 1159.42
   452.7 1159.34   462.3 1161.17   482.5 1175.77   492.5 1179.45   522.3 1200.70
   532.3 1201.42   552.2 1211.57   572.1 1217.08   601.9 1230.91   611.9 1231.50
   631.8 1240.44   651.7 1245.62   681.5 1259.31   691.5 1259.94   711.4 1269.10
   731.3 1274.79   761.1 1290.51   771.1 1291.18   791.0 1302.16   810.9 1308.65
   830.8 1320.72   840.7 1322.11   870.6 1339.35   890.5 1345.93   910.4 1357.58
#Mann= 3 , 0 , 0
       0     0.1       0   447.3   0.045       0   462.3     0.1       0
Bank Sta=   447.3,   462.3
Exp/Cntr=0.3,0.1

Type RM Length L Ch R = 1 ,32266.2,409.8,400,390.2
XS GIS Cut Line= 3
     1694391.399      398239.373     1694258.634      397803.980
     1694127.833      397368.254
#Sta/Elev= 30
     3.0 1257.99    77.7 1234.42    98.3 1225.88   108.6 1224.64   180.6 1199.04
   190.9 1197.95   221.7 1186.26   262.9 1174.63   334.9 1159.72   447.7 1152.17
   448.1 1152.12   462.7 1154.66   509.7 1177.24   520.0 1178.07   550.8 1195.07
   571.3 1201.85   591.9 1213.46   602.2 1214.60   633.0 1232.38   653.5 1238.95
   674.1 1249.52   684.4 1250.56   715.2 1266.69   735.7 1272.72   756.3 1283.71
   766.6 1284.72   787.1 1294.04   838.5 1311.43   889.8 1324.53   910.1 1332.17
#Mann= 3 , 0 , 0
       0     0.1       0   447.7   0.045       0   462.7     0.1       0
Bank Sta=   447.7,   462.7
Exp/Cntr=0.3,0.1

Type RM Length L Ch R = 1 ,31866.2,396.2,400,405.4
XS GIS Cut Line= 3
     1694912.895      397964.918     1694609.829      397625.545
     1694308.551      397284.570
#Sta/Elev= 30
     1.3 1190.69    35.1 1196.10    48.3 1193.86    75.2 1193.95   104.7 1186.16
   119.5 1187.54   163.8 1184.57   208.1 1175.17   237.7 1167.24   291.0 1159.27
   351.7 1152.12   444.1 1145.60   447.5 1145.78   462.5 1147.44   533.6 1173.63
   562.3 1188.06   575.4 1190.67   601.7 1203.09   622.7 1208.18   654.2 1222.13
   667.7 1225.01   697.0 1235.61   723.1 1241.30   756.5 1252.51   772.4 1255.13
   811.8 1270.62   824.9 1273.80   845.7 1283.51   860.5 1287.49   910.0 1306.27
#Mann= 3 , 0 , 0
       0     0.1       0   447.5   0.045       0   462.5     0.1       0
Bank Sta=   447.5,   462.5
Exp/Cntr=0.3,0.1

Type RM Length L Ch R = 1 ,31466.2,402.6,400,395.7
XS GIS Cut Line= 3
     1695133.415      397732.639     1694890.205      397346.161
     1694678.282      396943.854
#Sta/Elev= 30
     0.7 1265.03    27.7 1253.25    46.1 1248.99    58.8 1244.13    82.0 1232.42
    93.7 1230.42   128.5 1215.01   151.8 1207.99   175.1 1197.76   186.7 1195.08
   218.0 1180.62   233.2 1177.15   267.8 1161.42   279.7 1159.09   303.7 1147.01
   317.9 1144.87   449.1 1143.27   454.1 1143.16   464.1 1143.58   487.6 1147.79
   515.4 1150.70   576.5 1163.92   663.1 1176.17   726.5 1187.81   754.5 1199.30
   765.6 1201.48   843.5 1229.19   854.6 1230.54   887.9 1244.71   911.3 1250.53
#Mann= 3 , 0 , 0
       0     0.1       0   449.1   0.045       0   464.1     0.1       0
Bank Sta=   449.1,   464.1
Exp/Cntr=0.3,0.1

Type RM Length L Ch R = 1 ,31066.2,395.3,400,408.7
XS GIS Cut Line= 3
     1695510.397      397484.554     1695225.630      397129.684
     1694940.525      396775.085
#Sta/Elev= 30
     4.6 1284.33    23.3 1276.28    35.9 1273.76    59.9 1261.81    86.4 1252.76
   124.2 1236.46   136.8 1233.05   174.7 1215.29   187.3 1211.72   201.4 1204.95
   237.8 1191.81   275.6 1172.78   288.2 1169.49   358.6 1138.45   376.5 1136.03
   447.5 1133.98   452.2 1133.82   462.5 1134.33   540.6 1149.58   657.1 1179.88
   704.2 1198.31   719.9 1206.61   751.3 1217.59   780.5 1231.03   793.1 1233.83
   818.4 1244.66   843.6 1252.29   868.9 1264.28   894.1 1272.75   910.0 1280.00
#Mann= 3 , 0 , 0
       0     0.1       0   447.5   0.045       0   462.5     0.1       0
Bank Sta=   447.5,   462.5
Exp/Cntr=0.3,0.1

Type RM Length L Ch R = 1 ,30666.2,353.8,346.6,335.5
XS GIS Cut Line= 3
     1695739.939      397288.226     1695529.376      396871.156
     1695399.198      396437.424
#Sta/Elev= 30
     3.0 1264.19    65.0 1238.09    76.0 1236.62   109.0 1220.43   131.1 1214.21
   153.1 1203.26   164.2 1201.73   197.2 1185.10   219.3 1178.87   241.3 1167.60
   252.3 1166.28   307.5 1143.22   329.5 1131.60   362.6 1128.52   459.7 1128.42
   461.8 1128.26   474.7 1129.20   503.2 1139.65   595.7 1157.28   636.8 1168.58
   677.9 1184.14   708.7 1204.22   722.0 1209.09   749.8 1236.99   760.1 1242.19
   780.6 1268.09   790.9 1278.46   842.3 1298.43   873.1 1314.17   920.1 1329.03
#Mann= 3 , 0 , 0
       0     0.1       0   459.7   0.045       0   474.7     0.1       0
Bank Sta=   459.7,   474.7
Exp/Cntr=0.3,0.1

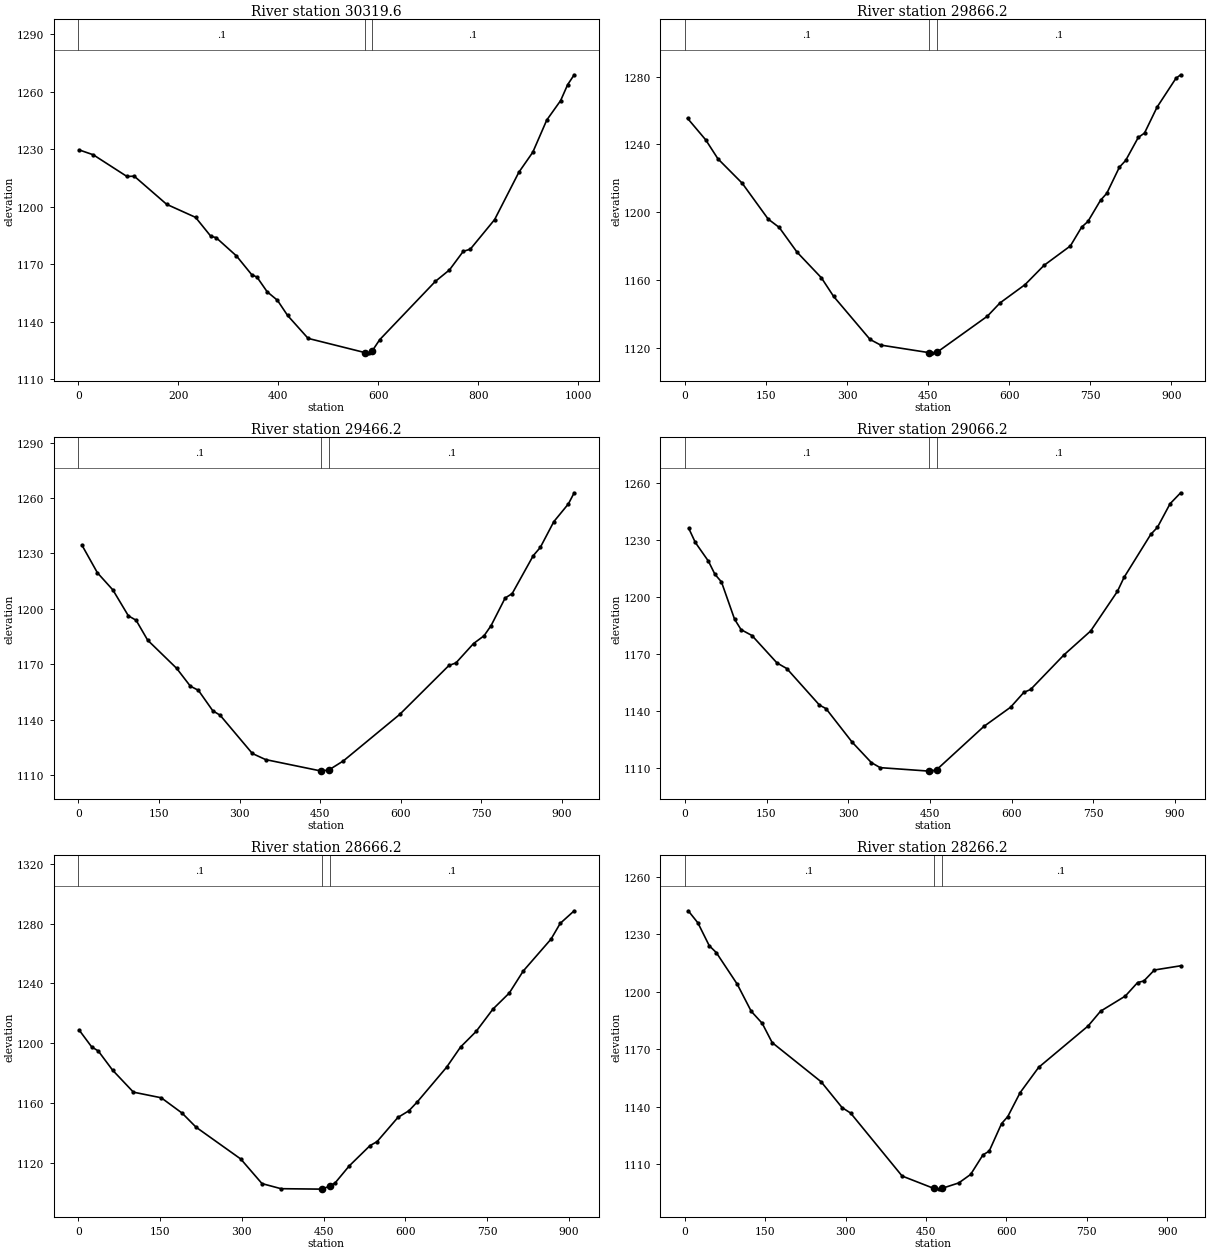
Type RM Length L Ch R = 1 ,30319.6,458.8,453.4,449.4
XS GIS Cut Line= 3
     1696026.912      397278.676     1695882.332      396773.400
     1695552.257      396443.523
#Sta/Elev= 30
     1.8 1229.67    29.9 1227.14    97.3 1215.83   111.8 1216.00   176.8 1201.31
   234.6 1194.52   265.3 1184.60   275.5 1183.99   316.5 1174.39   347.2 1164.56
   357.4 1163.41   377.9 1155.71   398.4 1151.29   418.8 1143.35   459.8 1131.42
     573 1124.04   582.5 1123.73     588 1124.86   603.1 1130.74   714.5 1161.15
   742.7 1167.12   770.2 1176.78   784.4 1177.93   833.0 1193.34   881.5 1218.02
   909.4 1228.47   937.4 1245.26   965.1 1255.39   979.2 1263.71   992.2 1268.83
#Mann= 3 , 0 , 0
       0     0.1       0     573   0.045       0     588     0.1       0
Bank Sta=     573,     588
Exp/Cntr=0.3,0.1

Type RM Length L Ch R = 1 ,29866.2,395.1,400,405.9
XS GIS Cut Line= 3
     1696520.371      396626.176     1696118.883      396403.253
     1695731.260      396159.394
#Sta/Elev= 30
     5.0 1255.45    38.8 1242.67    61.3 1231.51   106.3 1217.06   154.3 1195.90
   174.6 1191.01   207.6 1176.40   252.7 1161.23   275.2 1150.29   342.7 1124.83
   362.3 1121.51   451.7 1117.04   456.4 1116.75   466.7 1117.30   559.7 1138.56
   583.0 1146.37   629.5 1157.23   664.4 1168.56   713.3 1180.07   734.1 1191.17
   745.7 1194.50   769.0 1207.01   780.6 1211.14   803.9 1226.55   815.5 1230.53
   838.8 1244.11   850.4 1246.73   873.6 1262.02   908.5 1279.05   917.2 1281.12
#Mann= 3 , 0 , 0
       0     0.1       0   451.7   0.045       0   466.7     0.1       0
Bank Sta=   451.7,   466.7
Exp/Cntr=0.3,0.1

Type RM Length L Ch R = 1 ,29466.2,403.1,400,395.2
XS GIS Cut Line= 3
     1696679.085      396418.056     1696343.264      396104.204
     1696038.406      395756.033
#Sta/Elev= 30
     6.6 1234.54    35.5 1219.50    64.3 1210.21    93.1 1196.20   107.5 1193.80
   129.0 1183.01   182.9 1167.76   208.4 1158.09   223.3 1155.87   250.2 1144.75
   263.7 1142.38   323.7 1121.64   348.4 1118.33   452.2 1112.10   453.4 1112.08
   467.2 1112.92   493.2 1117.65   597.8 1142.78   689.4 1169.30   702.5 1170.69
   735.2 1181.18   754.8 1185.40   767.9 1190.92   794.0 1205.84   807.1 1208.25
   846.3 1228.78   859.4 1233.24   884.6 1247.22   911.7 1256.84   922.4 1262.82
#Mann= 3 , 0 , 0
       0     0.1       0   452.2   0.045       0   467.2     0.1       0
Bank Sta=   452.2,   467.2
Exp/Cntr=0.3,0.1

Type RM Length L Ch R = 1 ,29066.2,398.1,400,401.2
XS GIS Cut Line= 3
     1696964.783      396057.596     1696591.480      395797.540
     1696225.921      395526.212
#Sta/Elev= 30
     7.3 1236.28    19.3 1228.87    43.3 1219.01    55.3 1212.05    67.3 1208.03
    91.3 1188.39   103.3 1182.83   123.3 1179.73   169.2 1165.26   187.2 1162.30
   247.2 1143.01   259.2 1141.15   307.1 1123.48   342.4 1112.66   358.6 1109.98
   447.5 1108.16   451.1 1108.14   462.5 1108.93   549.0 1131.73   598.0 1141.87
   622.5 1149.73   634.8 1151.24   696.1 1169.52   745.1 1182.14   794.1 1203.00
   806.3 1210.39   855.4 1233.13   867.6 1236.83   890.8 1249.29   910.2 1255.06
#Mann= 3 , 0 , 0
       0     0.1       0   447.5   0.045       0   462.5     0.1       0
Bank Sta=   447.5,   462.5
Exp/Cntr=0.3,0.1

Type RM Length L Ch R = 1 ,28666.2,399.3,400,396.9
XS GIS Cut Line= 3
     1697203.904      395786.883     1696853.428      395496.725
     1696502.952      395206.567
#Sta/Elev= 30
     1.6 1208.78    24.4 1197.62    36.6 1194.85    62.8 1182.07   101.1 1167.33
   152.2 1163.57   190.5 1153.32   216.1 1143.91   298.1 1122.66   337.1 1106.22
   372.0 1102.82   446.0 1102.53   447.5 1102.56   462.5 1104.77   471.6 1106.82
   497.1 1118.01   535.4 1131.63   548.2 1134.24   586.5 1150.43   606.7 1154.89
   622.1 1160.82   675.9 1183.99   701.5 1197.49   730.1 1207.91   761.0 1222.87
   790.9 1233.56   816.5 1248.26   867.6 1269.63   884.4 1280.12   910.0 1288.51
#Mann= 3 , 0 , 0
       0     0.1       0   447.5   0.045       0   462.5     0.1       0
Bank Sta=   447.5,   462.5
Exp/Cntr=0.3,0.1

Type RM Length L Ch R = 1 ,28266.2,435.4,459.4,440.8
XS GIS Cut Line= 3
     1697426.149      395484.893     1697070.249      395175.415
     1696683.804      394938.620
#Sta/Elev= 30
     6.5 1242.32    24.4 1236.04    45.6 1224.10    58.7 1220.52    97.8 1204.00
   123.9 1189.84   144.4 1183.54   163.0 1173.46   254.3 1153.01   293.4 1139.51
   309.3 1136.66   405.4 1103.75   464.1 1097.33   475.0 1096.91   479.1 1097.26
   511.0 1100.14   533.2 1104.59   556.2 1114.80   567.8 1116.76   590.9 1131.14
   602.4 1134.78   625.5 1147.32   660.1 1160.54   752.4 1182.18   775.5 1189.86
   821.7 1197.78   844.7 1204.86   856.3 1205.67   876.0 1211.40   924.9 1213.60
#Mann= 3 , 0 , 0
       0     0.1       0   464.1   0.045       0   479.1     0.1       0
Bank Sta=   464.1,   479.1
Exp/Cntr=0.3,0.1

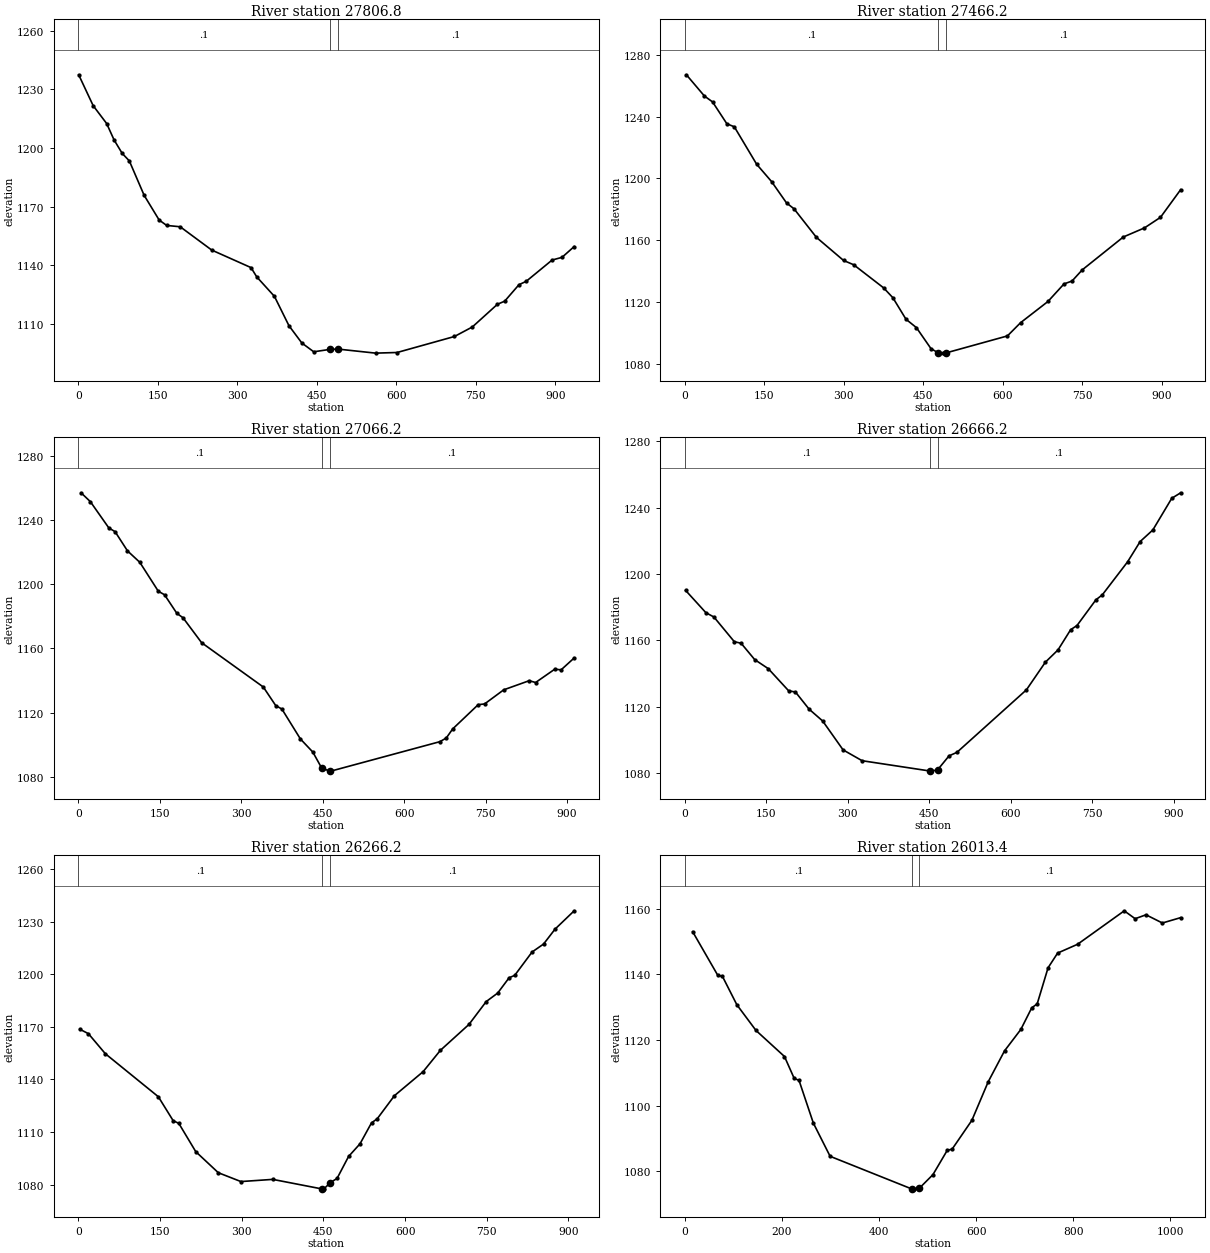
Type RM Length L Ch R = 1 ,27806.8,272.5,340.6,278.1
XS GIS Cut Line= 3
     1697596.078      395233.214     1697254.268      394879.296
     1696949.886      394556.793
#Sta/Elev= 30
     0.7 1237.43    28.0 1221.64    53.4 1212.52    67.5 1204.08    82.8 1197.21
    96.2 1193.39   124.2 1175.74   152.5 1163.11   166.7 1160.35   192.2 1159.67
   251.7 1147.74   325.8 1138.77   336.7 1133.99   370.0 1124.05   397.4 1109.03
   421.7 1100.19   444.1 1095.69   475.2 1096.93   490.2 1097.06   560.8 1095.00
   601.4 1095.32   709.6 1103.51   743.4 1108.39   790.8 1120.02   804.4 1121.58
   831.4 1130.03   844.9 1131.72   893.9 1142.64   912.6 1144.02   935.5 1149.53
#Mann= 3 , 0 , 0
       0     0.1       0   475.2   0.045       0   490.2     0.1       0
Bank Sta=   475.2,   490.2
Exp/Cntr=0.3,0.1

Type RM Length L Ch R = 1 ,27466.2,395.3,400,406.5
XS GIS Cut Line= 3
     1697783.473      395071.659     1697435.599      394732.294
     1697092.769      394440.574
#Sta/Elev= 30
     3.1 1266.99    37.1 1253.24    52.4 1249.46    79.4 1235.31    93.5 1233.33
   135.7 1209.07   163.9 1197.84   192.1 1184.02   206.2 1180.25   248.5 1161.75
   299.8 1146.78   318.9 1144.01   375.3 1129.07   392.8 1122.69   417.6 1108.74
   437.3 1103.31   464.8 1089.70   478.5 1086.99   488.2 1086.80   493.5 1086.97
   609.1 1097.94   634.0 1106.52   685.6 1120.23   715.9 1131.60   731.1 1133.48
   750.3 1140.69   827.9 1161.99   867.8 1167.87   898.1 1174.73   936.1 1192.61
#Mann= 3 , 0 , 0
       0     0.1       0   478.5   0.045       0   493.5     0.1       0
Bank Sta=   478.5,   493.5
Exp/Cntr=0.3,0.1

Type RM Length L Ch R = 1 ,27066.2,403.2,400,400.3
XS GIS Cut Line= 3
     1698009.282      394937.037     1697780.473      394542.726
     1697530.761      394159.678
#Sta/Elev= 30
     5.1 1256.78    22.2 1251.27    56.3 1234.87    67.7 1232.61    90.5 1220.65
   113.2 1213.53   147.3 1195.52   158.7 1193.34   181.5 1181.73   192.8 1179.00
   227.0 1163.50   340.7 1135.88   363.5 1124.35   374.9 1122.17   409.0 1103.55
   431.8 1095.42   448.4 1085.30   463.4 1083.57   465.0 1083.54   665.9 1101.88
   677.6 1104.16   689.4 1109.81   736.4 1124.92   748.1 1125.35   783.4 1134.15
   830.3 1139.83   842.1 1138.70   877.3 1146.98   889.1 1146.60   913.1 1153.97
#Mann= 3 , 0 , 0
       0     0.1       0   448.4   0.045       0   463.4     0.1       0
Bank Sta=   448.4,   463.4
Exp/Cntr=0.3,0.1

Type RM Length L Ch R = 1 ,26666.2,392.2,400,404.5
XS GIS Cut Line= 3
     1698348.734      394645.102     1698066.226      394285.030
     1697824.020      393900.410
#Sta/Elev= 30
     1.4 1190.14    38.8 1176.69    53.6 1174.08    91.1 1159.22   103.6 1158.28
   128.6 1148.44   153.6 1142.98   191.1 1129.64   203.6 1128.92   228.7 1118.60
   253.7 1111.46   291.2 1094.08   326.2 1087.56   450.2 1081.40   453.8 1081.29
   465.2 1082.10   486.2 1090.50   500.6 1092.58   628.5 1130.23   663.4 1146.90
   686.6 1154.27   709.9 1166.46   721.5 1168.94   756.4 1184.46   768.0 1187.38
   814.5 1207.25   837.8 1219.54   861.1 1226.50   895.9 1245.57   912.2 1248.86
#Mann= 3 , 0 , 0
       0     0.1       0   450.2   0.045       0   465.2     0.1       0
Bank Sta=   450.2,   465.2
Exp/Cntr=0.3,0.1

Type RM Length L Ch R = 1 ,26266.2,247.4,252.8,259.1
XS GIS Cut Line= 3
     1698563.525      394541.834     1698419.800      394109.587
     1698257.770      393684.513
#Sta/Elev= 30
     2.7 1168.65    18.5 1166.12    49.6 1154.67   146.9 1130.12   174.1 1116.46
   184.5 1114.91   215.6 1098.78   257.0 1086.75   298.5 1081.70   357.0 1082.94
     448 1077.45   450.4 1077.38     463 1081.14   475.1 1083.51   496.2 1096.02
   517.2 1103.25   538.3 1115.19   548.8 1117.54   580.4 1130.72   633.1 1144.44
   664.7 1156.58   717.3 1171.41   748.9 1184.44   770.0 1189.30   791.0 1198.05
   801.2 1199.39   833.1 1212.72   854.2 1217.27   875.3 1225.79   910.4 1236.24
#Mann= 3 , 0 , 0
       0     0.1       0     448   0.045       0     463     0.1       0
Bank Sta=     448,     463
Exp/Cntr=0.3,0.1

Type RM Length L Ch R = 1 ,26013.4,564.7,547.2,535.1
XS GIS Cut Line= 3
     1698680.360      394523.062     1698652.648      393943.689
     1698441.382      393556.368
#Sta/Elev= 30
    16.2 1153.00    67.8 1139.74    77.6 1139.37   107.2 1130.74   146.6 1122.91
   205.3 1114.97   225.4 1108.27   235.2 1107.72   264.8 1094.67   299.3 1084.56
   468.2 1074.57   471.7 1074.56   483.2 1074.85   511.1 1078.98   540.6 1086.40
   550.5 1086.73   591.3 1095.53   624.9 1107.27   658.5 1116.69   692.1 1123.22
   714.5 1129.79   725.8 1131.02   748.2 1142.01   767.9 1146.49   809.0 1149.17
   905.1 1159.36   927.5 1156.96   949.9 1158.15   983.6 1155.65  1021.2 1157.28
#Mann= 3 , 0 , 0
       0     0.1       0   468.2   0.045       0   483.2     0.1       0
Bank Sta=   468.2,   483.2
Exp/Cntr=0.3,0.1

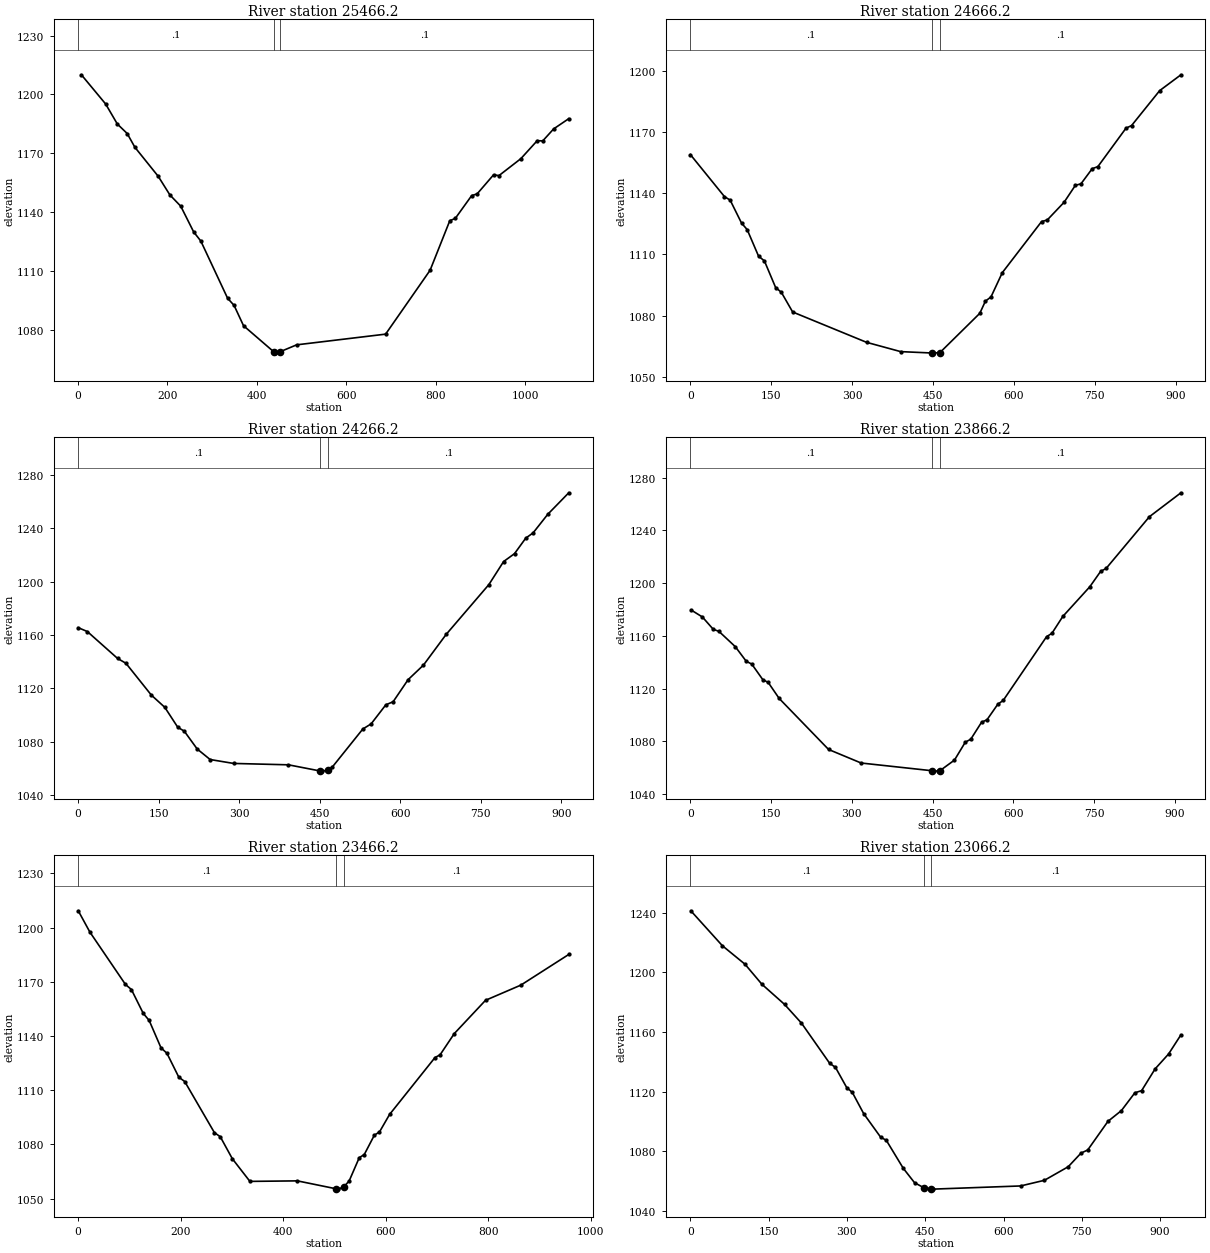
Type RM Length L Ch R = 1 ,25466.2,800.7,800,785.5
XS GIS Cut Line= 3
     1699445.574      394193.086     1699110.195      393900.410
     1698723.070      393375.283
#Sta/Elev= 30
     7.5 1209.96    61.7 1195.07    87.8 1184.86   109.9 1180.01   127.0 1173.02
   179.3 1158.17   205.4 1148.67   229.7 1142.92   258.5 1129.82   274.6 1125.13
   334.4 1095.99   349.0 1092.30   370.1 1081.94   437.6 1068.66   440.5 1067.96
   452.6 1068.74   488.9 1072.19   687.9 1077.65   787.4 1110.24   831.5 1135.55
   843.7 1136.68   880.4 1148.34   892.6 1149.21   929.3 1158.92   941.5 1158.55
   990.4 1167.18  1027.1 1176.38  1039.3 1176.22  1063.7 1182.36  1097.5 1187.58
#Mann= 3 , 0 , 0
       0     0.1       0   437.6   0.045       0   452.6     0.1       0
Bank Sta=   437.6,   452.6
Exp/Cntr=0.3,0.1

Type RM Length L Ch R = 1 ,24666.2,394.3,400,409.9
XS GIS Cut Line= 3
     1699733.885      393432.164     1699308.628      393269.301
     1698879.155      393119.194
#Sta/Elev= 30
     0.3 1159.00    63.5 1138.36    74.0 1136.66    95.1 1125.39   105.6 1122.17
   126.7 1109.13   137.5 1106.83   158.3 1093.76   168.9 1091.41   189.9 1081.74
   326.9 1066.85   390.1 1062.29   447.9 1061.61   449.8 1061.55   462.9 1061.81
   536.8 1081.08   547.2 1087.05   557.6 1089.15   578.5 1101.03   651.4 1126.15
   661.8 1126.88   693.1 1135.60   714.0 1143.91   724.4 1144.66   745.2 1152.08
   755.7 1153.09   807.8 1171.95   818.2 1173.26   870.3 1190.40   909.6 1198.15
#Mann= 3 , 0 , 0
       0     0.1       0   447.9   0.045       0   462.9     0.1       0
Bank Sta=   447.9,   462.9
Exp/Cntr=0.3,0.1

Type RM Length L Ch R = 1 ,24266.2,408,400,387.2
XS GIS Cut Line= 3
     1699855.668      393186.174     1699481.244      392920.968
     1699154.558      392603.908
#Sta/Elev= 30
     0.3 1165.54    17.3 1162.62    73.5 1142.50    89.2 1138.82   136.5 1114.97
   161.6 1105.79   185.7 1090.86   197.8 1087.95   221.9 1074.56   246.0 1066.67
   289.7 1063.74   391.9 1062.70   451.3 1058.05   454.7 1057.97   466.3 1058.86
   473.9 1061.18   530.4 1089.54   545.9 1093.40   573.3 1107.70   586.9 1110.00
   614.8 1126.56   643.4 1137.48   685.8 1160.55   765.3 1197.87   792.7 1215.13
   813.0 1221.04   833.9 1232.66   847.6 1236.60   875.0 1250.57   914.0 1266.65
#Mann= 3 , 0 , 0
       0     0.1       0   451.3   0.045       0   466.3     0.1       0
Bank Sta=   451.3,   466.3
Exp/Cntr=0.3,0.1

Type RM Length L Ch R = 1 ,23866.2,392.1,400,396.2
XS GIS Cut Line= 3
     1700099.833      392687.187     1699659.433      392569.742
     1699213.983      392477.692
#Sta/Elev= 30
     2.2 1179.57    22.6 1174.40    42.9 1164.99    53.1 1163.57    83.7 1151.88
   104.0 1140.80   114.2 1138.71   134.6 1126.95   144.8 1124.74   165.1 1112.63
   256.8 1073.95   317.2 1063.68   448.3 1057.85   460.4 1057.53   463.3 1057.81
   490.5 1065.91   510.6 1079.51   520.7 1081.71   540.8 1094.63   550.8 1096.46
   570.9 1108.25   581.0 1111.18   661.4 1159.47   671.4 1162.06   691.5 1174.80
   741.7 1197.34   761.8 1209.02   771.9 1211.20   852.3 1250.45   910.7 1268.55
#Mann= 3 , 0 , 0
       0     0.1       0   448.3   0.045       0   463.3     0.1       0
Bank Sta=   448.3,   463.3
Exp/Cntr=0.3,0.1

Type RM Length L Ch R = 1 ,23466.2,400.5,400,421.9
XS GIS Cut Line= 3
     1700196.050      392468.348     1699761.123      392200.251
     1699315.679      392180.446
#Sta/Elev= 30
     0.4 1209.23    23.0 1197.48    92.4 1168.50   104.0 1165.69   127.1 1152.49
   138.6 1148.61   161.7 1133.45   173.3 1130.42   196.4 1117.22   208.0 1114.79
   265.8 1086.55   277.3 1084.25   300.8 1072.09   335.1 1059.55   427.6 1059.84
   503.4 1055.44   507.6 1055.27   518.4 1056.61   528.6 1059.78   548.3 1072.66
   558.1 1074.41   577.8 1085.14   587.7 1086.87   607.4 1096.56   696.0 1128.06
   705.9 1129.56   733.6 1141.31   794.5 1159.72   863.5 1168.14   956.8 1185.08
#Mann= 3 , 0 , 0
       0     0.1       0   503.4   0.045       0   518.4     0.1       0
Bank Sta=   503.4,   518.4
Exp/Cntr=0.3,0.1

Type RM Length L Ch R = 1 ,23066.2,392.9,400,377.7
XS GIS Cut Line= 3
     1700419.349      392192.677     1700006.342      392003.250
     1699692.571      391632.913
#Sta/Elev= 30
     1.2 1241.38    61.6 1217.95   104.9 1205.55   137.3 1192.09   180.6 1178.61
   213.1 1166.01   267.2 1138.99   278.1 1136.37   299.7 1122.76   310.5 1119.49
   332.2 1105.28   364.7 1089.47   375.5 1087.40   408.0 1068.60   429.6 1058.93
   446.9 1055.66   461.9 1054.64   464.7 1054.62   632.7 1056.75   678.3 1060.54
   724.0 1069.66   748.4 1078.78   761.3 1080.90   800.0 1100.09   825.8 1107.33
   851.6 1119.28   864.5 1120.70   890.3 1135.29   916.1 1145.29   939.7 1158.10
#Mann= 3 , 0 , 0
       0     0.1       0   446.9   0.045       0   461.9     0.1       0
Bank Sta=   446.9,   461.9
Exp/Cntr=0.3,0.1