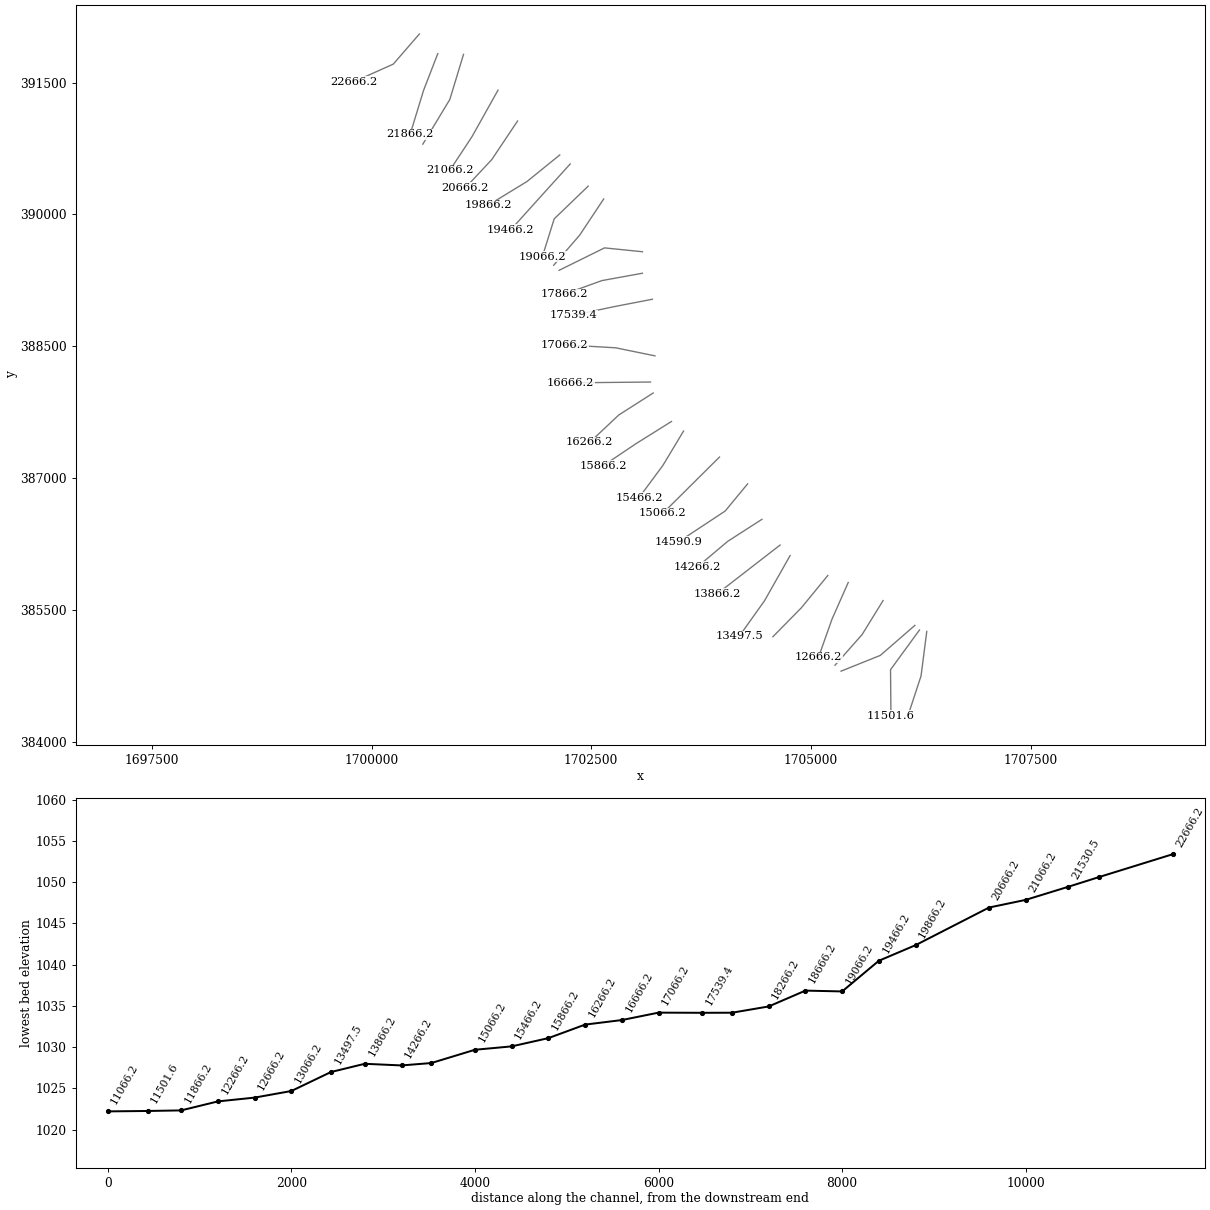
HEC-RAS study BrthlmwFrk.prj: BrthlmwFrk

--- BrthlmwFrk.g01 (geometry) --- (continued)

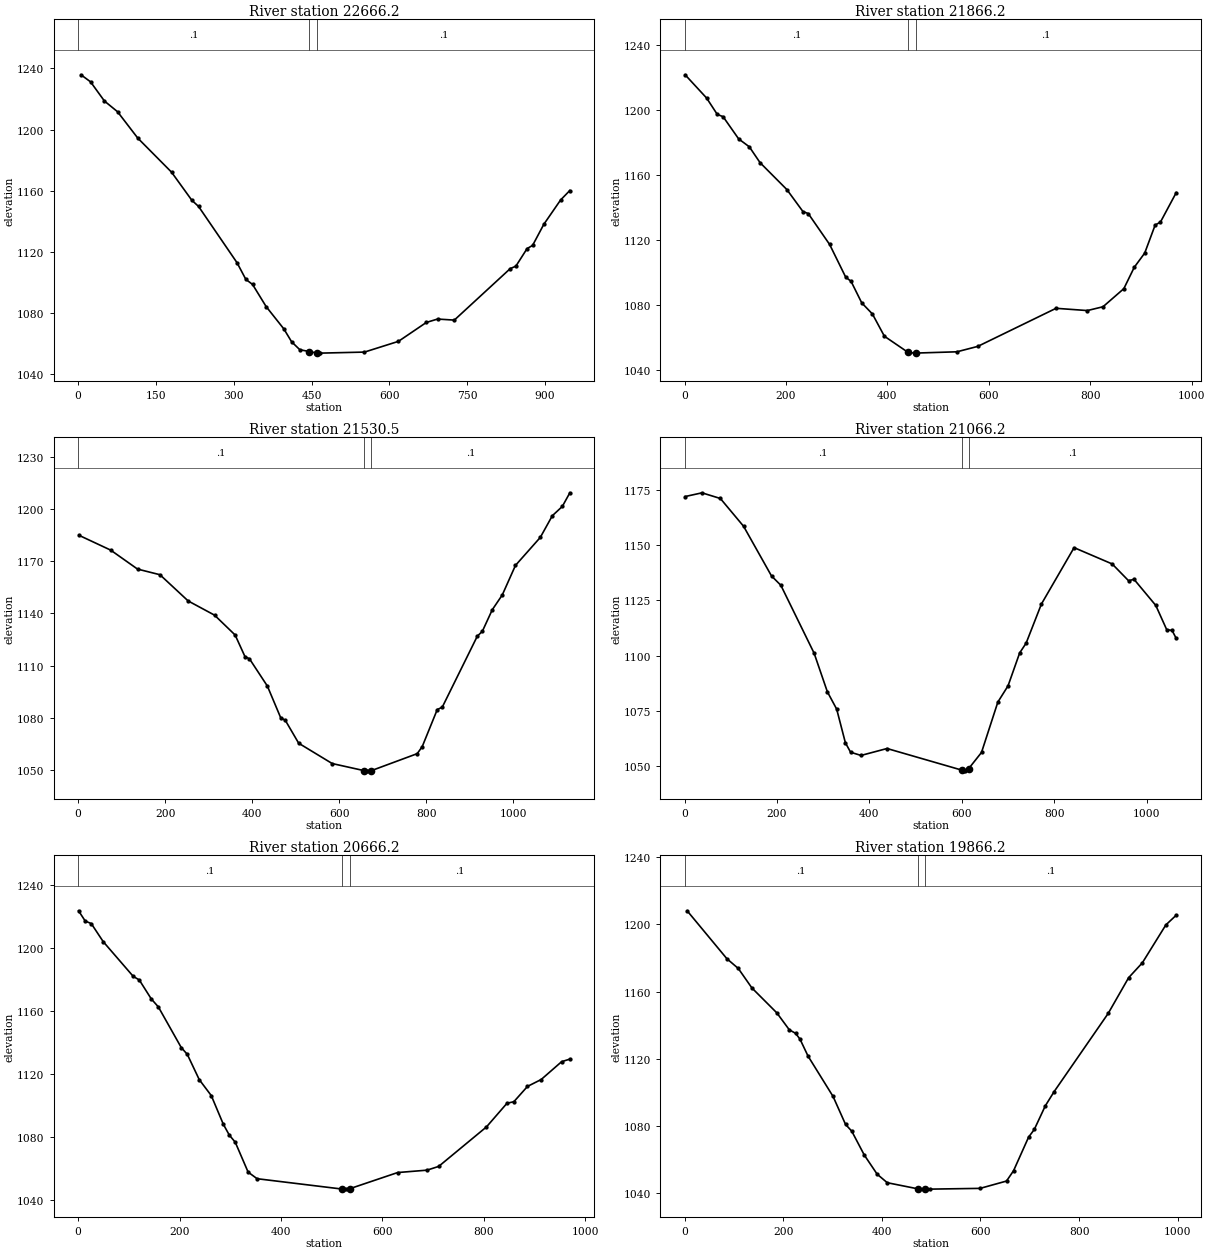
Type RM Length L Ch R = 1 ,22666.2,705.5,800,810.8
XS GIS Cut Line= 3
     1700544.179      392052.756     1700247.666      391710.270
     1699796.103      391508.416
#Sta/Elev= 30
     5.6 1235.85    23.9 1231.27    50.7 1218.67    75.9 1211.68   115.0 1194.34
   180.0 1172.04   219.1 1153.62   232.1 1149.56   306.3 1112.63   323.2 1101.75
   336.2 1098.41   362.3 1083.92   396.5 1069.25   411.5 1060.79   427.3 1055.61
   445.5 1054.44   460.5 1053.41   466.4 1053.39   551.8 1054.07   617.3 1061.11
   671.1 1073.51   692.7 1075.73   725.0 1075.04   832.8 1108.81   843.6 1110.40
   865.2 1121.91   875.9 1124.04   897.5 1137.86   929.8 1153.79   947.6 1160.01
#Mann= 3 , 0 , 0
       0     0.1       0   445.5   0.045       0   460.5     0.1       0
Bank Sta=   445.5,   460.5
Exp/Cntr=0.3,0.1

Type RM Length L Ch R = 1 ,21866.2,338.2,335.7,331.3
XS GIS Cut Line= 3
     1700754.053      391829.217     1700592.153      391411.073
     1700439.874      390912.453
#Sta/Elev= 30
     1.2 1221.87    43.4 1207.61    64.5 1197.52    76.0 1196.11   106.7 1182.44
   127.7 1177.58   148.9 1167.82   201.7 1151.29   233.4 1137.76   243.9 1136.52
   286.1 1117.48   317.8 1097.36   328.3 1094.83   349.4 1081.56   370.5 1074.70
   394.1 1061.02   440.9 1051.07   453.9 1050.63   455.9 1050.66   537.1 1051.45
   578.2 1054.77   732.6 1078.21   794.3 1076.82   825.2 1079.16   866.3 1090.30
   886.9 1103.47   907.5 1112.21   928.1 1129.48   938.4 1131.21   969.7 1149.43
#Mann= 3 , 0 , 0
       0     0.1       0   440.9   0.045       0   455.9     0.1       0
Bank Sta=   440.9,   455.9
Exp/Cntr=0.3,0.1

Type RM Length L Ch R = 1 ,21530.5,462.8,464.3,463.4
XS GIS Cut Line= 3
     1701046.998      391820.968     1700891.063      391307.893
     1700584.224      390799.848
#Sta/Elev= 30
     2.8 1184.77    74.8 1176.36   136.5 1165.47   188.0 1162.23   252.8 1147.18
   313.5 1139.01   360.8 1127.60   383.4 1115.19   393.7 1113.95   434.8 1098.31
   465.6 1080.02   475.9 1078.69   506.8 1065.47   583.8 1053.80   657.8 1049.69
   664.3 1049.45   672.8 1049.64   779.2 1059.49   790.7 1063.56   825.2 1084.81
   836.7 1086.18   917.2 1126.94   928.8 1129.74   951.6 1142.12   974.6 1150.62
  1004.9 1167.59  1062.0 1183.68  1089.6 1196.11  1112.6 1201.46  1129.8 1209.26
#Mann= 3 , 0 , 0
       0     0.1       0   657.8   0.045       0   672.8     0.1       0
Bank Sta=   657.8,   672.8
Exp/Cntr=0.3,0.1

Type RM Length L Ch R = 1 ,21066.2,370.7,400,390.4
XS GIS Cut Line= 3
     1701439.349      391413.526     1701142.513      390883.270
     1700891.022      390501.986
#Sta/Elev= 30
     1.6 1171.98    37.7 1173.64    77.5 1171.08   127.8 1158.51   188.2 1136.07
   208.4 1131.86   280.5 1101.13   309.1 1083.72   329.3 1075.87   348.1 1060.69
   359.4 1056.40   382.0 1054.95   438.3 1058.08   600.2 1048.31   607.5 1047.86
   615.2 1049.03   642.8 1056.31   678.2 1079.08   700.2 1086.39   725.4 1101.28
   739.4 1105.71   772.5 1123.39   843.2 1148.87   925.7 1141.49   961.1 1133.92
   972.9 1134.56  1020.1 1122.74  1043.6 1111.84  1055.4 1111.42  1064.4 1107.81
#Mann= 3 , 0 , 0
       0     0.1       0   600.2   0.045       0   615.2     0.1       0
Bank Sta=   600.2,   615.2
Exp/Cntr=0.3,0.1

Type RM Length L Ch R = 1 ,20666.2,800.6,800,756.2
XS GIS Cut Line= 3
     1701661.644      391062.394     1701368.260      390623.511
     1701066.200      390301.005
#Sta/Elev= 30
     0.9 1223.53    14.0 1217.04    25.9 1215.45    49.5 1203.96   108.7 1181.93
   120.6 1179.67   144.2 1167.67   158.2 1162.57   203.4 1136.77   215.3 1132.46
   238.9 1116.41   262.6 1106.30   286.3 1088.15   298.1 1081.25   309.9 1076.70
   335.3 1057.72   353.0 1053.54   520.4 1046.98   527.9 1046.93   535.4 1047.16
   630.2 1057.45   688.0 1058.96   711.1 1061.34   805.4 1086.41   845.9 1101.43
   859.4 1102.39   886.3 1112.11   913.3 1116.49   953.7 1127.82   969.8 1129.43
#Mann= 3 , 0 , 0
       0     0.1       0   520.4   0.045       0   535.4     0.1       0
Bank Sta=   520.4,   535.4
Exp/Cntr=0.3,0.1

Type RM Length L Ch R = 1 ,19866.2,397.8,400,404.2
XS GIS Cut Line= 3
     1702142.243      390676.544     1701769.291      390374.516
     1701328.085      390104.935
#Sta/Elev= 30
     5.3 1208.13    85.8 1179.61   109.0 1173.78   136.5 1162.21   187.1 1147.35
   212.4 1137.25   225.1 1135.17   234.1 1131.68   250.4 1121.58   301.1 1097.57
   326.4 1080.93   339.0 1076.89   364.4 1062.67   390.5 1051.27   411.0 1046.19
   472.4 1042.58   487.4 1042.40   497.6 1042.37   599.3 1042.82   652.8 1047.18
   667.1 1053.34   697.6 1073.36   709.1 1077.89   731.5 1092.00   749.4 1100.47
   859.0 1147.04   900.4 1168.30   928.2 1177.15   975.9 1199.74   997.0 1205.55
#Mann= 3 , 0 , 0
       0     0.1       0   472.4   0.045       0   487.4     0.1       0
Bank Sta=   472.4,   487.4
Exp/Cntr=0.3,0.1

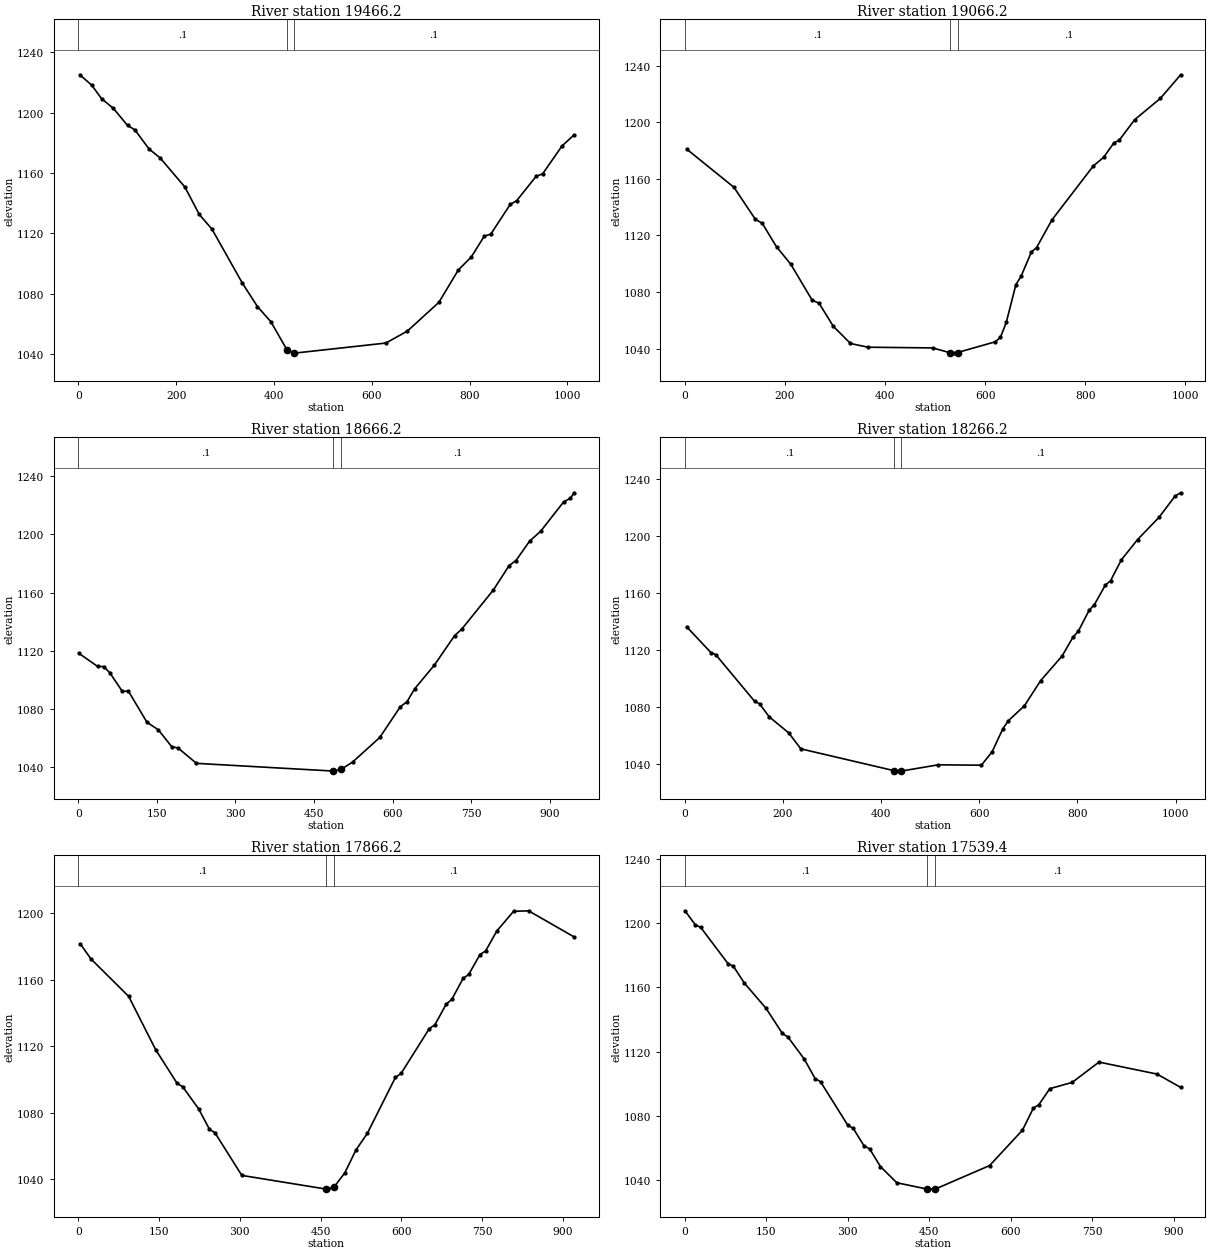
Type RM Length L Ch R = 1 ,19466.2,402.1,400,410.4
XS GIS Cut Line= 3
     1702261.251      390574.296     1701969.906      390252.598
     1701581.602      389822.099
#Sta/Elev= 30
     3.2 1225.03    27.4 1218.16    47.6 1209.20    71.4 1202.86   100.7 1191.43
   115.4 1188.62   144.7 1175.81   167.0 1170.03   218.0 1150.57   247.3 1132.43
   273.2 1122.72   335.3 1086.94   366.2 1071.37   393.9 1061.21   426.5 1042.68
   441.5 1040.51   442.0 1040.48   628.9 1047.16   672.9 1055.13   737.3 1074.18
   777.1 1095.70   803.6 1104.28   830.1 1118.08   843.4 1119.40   883.1 1139.09
   896.4 1141.63   936.1 1157.75   949.4 1159.38   989.1 1177.91  1013.8 1185.25
#Mann= 3 , 0 , 0
       0     0.1       0   426.5   0.045       0   441.5     0.1       0
Bank Sta=   426.5,   441.5
Exp/Cntr=0.3,0.1

Type RM Length L Ch R = 1 ,19066.2,389.9,400,388.1
XS GIS Cut Line= 3
     1702465.632      390321.793     1702078.674      389949.043
     1701943.426      389516.532
#Sta/Elev= 30
     3.9 1180.98    98.2 1154.00   140.7 1131.53   154.9 1128.49   183.3 1111.85
   211.6 1099.70   254.2 1074.32   268.4 1071.92   296.7 1055.71   331.0 1043.57
   365.8 1040.95   495.3 1040.44   529.8 1037.02   537.3 1036.76   544.8 1037.19
   620.2 1044.76   630.5 1047.91   642.2 1058.46   661.4 1085.18   671.7 1090.99
   692.4 1108.35   702.7 1111.36   733.6 1131.06   816.1 1169.11   836.7 1175.19
   857.3 1185.46   867.6 1187.19   898.6 1201.78   950.1 1216.92   990.5 1233.54
#Mann= 3 , 0 , 0
       0     0.1       0   529.8   0.045       0   544.8     0.1       0
Bank Sta=   529.8,   544.8
Exp/Cntr=0.3,0.1

Type RM Length L Ch R = 1 ,18666.2,428.5,400,370.4
XS GIS Cut Line= 3
     1702642.269      390175.905     1702368.604      389763.890
     1702073.077      389421.758
#Sta/Elev= 30
     1.1 1118.08    36.6 1109.10    48.4 1108.92    60.2 1104.65    83.8 1091.95
    95.6 1091.99   131.1 1070.52   152.8 1065.34   178.3 1053.70   190.1 1052.87
   225.6 1042.22   487.1 1036.90   487.6 1036.86   502.1 1038.18   523.5 1043.06
   575.6 1060.08   614.6 1081.18   627.6 1084.74   641.9 1093.47   679.6 1109.88
   718.6 1130.36   731.6 1134.54   792.4 1161.74   822.5 1178.55   835.6 1182.07
   861.6 1195.41   882.7 1202.24   926.6 1222.46   939.6 1225.06   946.7 1228.73
#Mann= 3 , 0 , 0
       0     0.1       0   487.1   0.045       0   502.1     0.1       0
Bank Sta=   487.1,   502.1
Exp/Cntr=0.3,0.1

Type RM Length L Ch R = 1 ,18266.2,393.5,400,395.9
XS GIS Cut Line= 3
     1703083.075      389575.300     1702651.770      389619.142
     1702134.600      389364.006
#Sta/Elev= 30
     3.9 1136.11    53.3 1118.07    63.2 1116.57   142.3 1083.89   152.2 1082.22
   172.0 1073.01   211.6 1061.80   236.4 1050.56     426 1035.29   439.7 1034.94
     441 1034.98   516.5 1039.37   604.2 1039.09   626.2 1048.53   648.1 1064.72
   659.1 1070.24   692.0 1080.77   724.9 1098.36   768.8 1115.71   790.8 1128.84
   801.7 1133.01   823.7 1147.69   834.7 1151.79   856.6 1165.28   867.5 1168.48
   889.5 1183.14   922.4 1197.27   966.3 1213.00   999.2 1227.96  1010.2 1230.11
#Mann= 3 , 0 , 0
       0     0.1       0     426   0.045       0     441     0.1       0
Bank Sta=     426,     441
Exp/Cntr=0.3,0.1

Type RM Length L Ch R = 1 ,17866.2,326.6,326.8,323.7
XS GIS Cut Line= 3
     1703082.648      389330.604     1702622.275      389247.074
     1702196.449      389093.347
#Sta/Elev= 30
     3.5 1181.70    23.5 1172.56    93.5 1150.05   143.5 1118.07   183.5 1097.74
   193.5 1095.84   223.5 1082.38   243.5 1070.12   253.5 1068.15   303.5 1042.43
   460.4 1034.19   463.5 1034.18   475.4 1035.73   494.7 1043.91   515.6 1057.80
   536.5 1067.64   588.8 1101.37   599.3 1103.75   651.6 1130.67   662.1 1133.03
   683.0 1145.37   693.4 1148.25   714.4 1160.86   724.8 1163.24   745.8 1175.23
   756.2 1177.39   777.1 1189.43   808.1 1201.21   836.0 1201.51   920.6 1185.80
#Mann= 3 , 0 , 0
       0     0.1       0   460.4   0.045       0   475.4     0.1       0
Bank Sta=   460.4,   475.4
Exp/Cntr=0.3,0.1

Type RM Length L Ch R = 1 ,17539.4,482,473.2,467.2
XS GIS Cut Line= 3
     1703196.521      389034.697     1702750.273      388948.327
     1702302.537      388853.493
#Sta/Elev= 30
     0.3 1207.76    19.2 1199.12    29.3 1197.41    79.4 1174.89    89.4 1173.18
   109.4 1162.78   149.5 1146.92   179.6 1131.26   189.6 1129.11   219.7 1115.34
   239.7 1103.15   249.8 1101.12   299.9 1074.02   309.9 1072.05   329.9 1061.11
   340.0 1059.32   360.0 1048.19   390.1 1038.14   445.6 1034.22   457.4 1034.17
   460.6 1034.18   560.8 1048.87   621.2 1070.94   641.3 1084.71   651.4 1086.83
   671.5 1096.84   712.6 1100.72   762.0 1113.41   868.8 1105.93   912.2 1097.63
#Mann= 3 , 0 , 0
       0     0.1       0   445.6   0.045       0   460.6     0.1       0
Bank Sta=   445.6,   460.6
Exp/Cntr=0.3,0.1

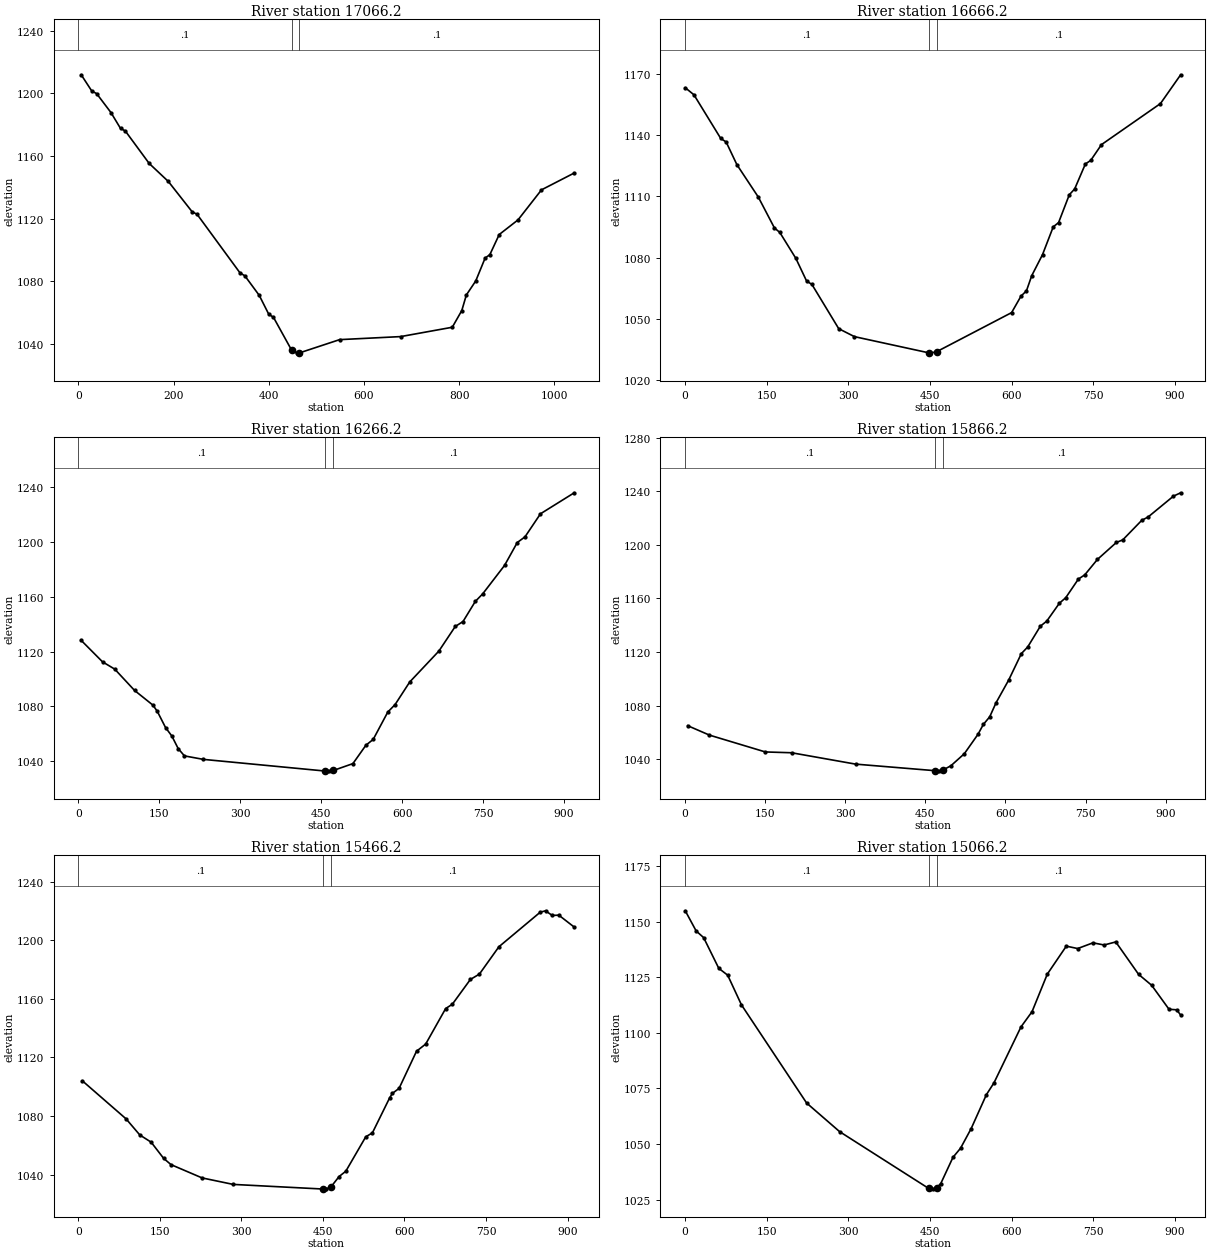
Type RM Length L Ch R = 1 ,17066.2,395.2,400,401.5
XS GIS Cut Line= 3
     1703225.052      388390.635     1702778.853      388482.058
     1702193.871      388516.162
#Sta/Elev= 30
     6.1 1211.79    28.3 1201.43    38.4 1199.82    68.5 1187.72    88.6 1177.58
    98.6 1175.99   148.8 1155.24   189.0 1143.75   239.2 1124.33   249.3 1122.83
   339.7 1085.34   349.7 1083.54   379.9 1071.08   400.0 1058.98   409.8 1057.07
     448 1036.07   460.1 1034.19     463 1034.20   548.8 1042.80   677.0 1044.74
   785.4 1050.70   805.4 1061.36   815.0 1071.32   834.7 1080.25   854.4 1094.88
   864.3 1097.02   884.0 1109.88   923.4 1119.19   972.8 1138.39  1041.4 1149.11
#Mann= 3 , 0 , 0
       0     0.1       0     448   0.045       0     463     0.1       0
Bank Sta=     448,     463
Exp/Cntr=0.3,0.1

Type RM Length L Ch R = 1 ,16666.2,387.4,400,416.9
XS GIS Cut Line= 3
     1703174.801      388092.716     1702719.825      388088.032
     1702264.850      388083.347
#Sta/Elev= 30
     1.0 1163.07    16.8 1159.65    66.0 1138.28    75.9 1136.57    95.6 1125.48
   134.9 1109.63   164.5 1094.52   174.3 1092.35   203.8 1079.65   223.5 1068.57
   233.3 1066.89   282.5 1045.25   311.4 1041.35   447.5 1033.45   450.6 1033.29
   462.5 1034.02   599.8 1053.11   617.1 1061.20   627.0 1063.73   636.8 1071.21
   656.5 1081.45   676.2 1095.06   686.0 1097.13   705.7 1110.77   715.5 1113.58
   735.2 1125.82   745.0 1127.56   764.7 1135.27   873.0 1155.36   910.0 1169.42
#Mann= 3 , 0 , 0
       0     0.1       0   447.5   0.045       0   462.5     0.1       0
Bank Sta=   447.5,   462.5
Exp/Cntr=0.3,0.1

Type RM Length L Ch R = 1 ,16266.2,400.2,400,396.2
XS GIS Cut Line= 3
     1703205.596      387967.789     1702813.837      387717.590
     1702483.451      387406.492
#Sta/Elev= 30
     4.8 1128.41    44.8 1112.55    67.5 1107.20   104.1 1091.68   138.3 1080.89
   146.3 1076.38   161.6 1064.54   173.3 1058.34   185.0 1049.19   196.6 1043.86
   231.8 1041.31   457.3 1032.80   464.8 1032.74   472.3 1033.20   508.7 1038.23
   532.8 1051.65   546.3 1055.91   573.3 1075.85   586.9 1081.37   613.9 1097.80
   668.0 1120.41   698.3 1138.36   712.7 1141.97   735.5 1156.68   749.1 1162.15
   789.6 1182.92   813.2 1199.66   827.5 1203.80   856.2 1220.64   918.6 1235.95
#Mann= 3 , 0 , 0
       0     0.1       0   457.3   0.045       0   472.3     0.1       0
Bank Sta=   457.3,   472.3
Exp/Cntr=0.3,0.1

Type RM Length L Ch R = 1 ,15866.2,389.4,400,407.7
XS GIS Cut Line= 3
     1703413.604      387643.793     1703009.592      387391.066
     1702635.105      387139.394
#Sta/Elev= 30
     5.3 1065.02    46.2 1057.96   150.7 1045.41   199.8 1044.81   319.5 1036.33
     469 1031.40   475.6 1031.10     484 1032.13   497.9 1035.11   523.0 1044.08
   548.6 1058.59   558.6 1065.95   570.5 1071.63   582.3 1082.07   606.0 1099.05
   629.7 1118.78   641.6 1123.74   665.3 1139.27   677.2 1143.01   700.9 1156.40
   712.7 1160.47   736.4 1174.40   748.3 1177.53   772.0 1189.04   807.6 1201.75
   819.4 1203.62   855.0 1218.24   866.9 1220.73   914.3 1236.28   927.7 1238.75
#Mann= 3 , 0 , 0
       0     0.1       0     469   0.045       0     484     0.1       0
Bank Sta=     469,     484
Exp/Cntr=0.3,0.1

Type RM Length L Ch R = 1 ,15466.2,405.6,400,396.6
XS GIS Cut Line= 3
     1703550.795      387534.481     1703314.969      387142.350
     1703044.279      386777.196
#Sta/Elev= 30
     7.6 1103.97    87.9 1078.04   113.1 1067.06   133.9 1062.17   156.8 1051.15
   170.4 1046.84   227.6 1037.76   284.9 1033.32   450.1 1030.16   455.4 1030.10
   465.1 1031.79   479.7 1038.71   492.0 1042.30   528.7 1065.80   541.0 1068.54
   572.5 1092.27   577.7 1095.46   590.0 1098.87   622.1 1124.23   639.0 1129.15
   675.7 1153.37   688.0 1156.32   721.2 1173.24   737.8 1176.90   773.7 1195.57
   849.8 1219.19   859.4 1220.09   871.7 1216.96   883.9 1217.12   912.1 1209.03
#Mann= 3 , 0 , 0
       0     0.1       0   450.1   0.045       0   465.1     0.1       0
Bank Sta=   450.1,   465.1
Exp/Cntr=0.3,0.1

Type RM Length L Ch R = 1 ,15066.2,479.3,475.3,471.3
XS GIS Cut Line= 3
     1703959.888      387239.082     1703637.022      386918.485
     1703314.156      386597.888
#Sta/Elev= 30
     0.9 1154.98    20.8 1145.93    34.6 1142.91    62.4 1129.08    78.7 1126.01
   104.0 1112.64   223.6 1068.45   284.2 1055.56   447.5 1030.02   455.0 1029.69
   462.5 1030.42   469.8 1032.20   492.2 1044.01   506.1 1048.11   525.6 1056.96
   553.6 1072.25   567.5 1077.56   617.0 1102.72   637.3 1109.57   665.3 1126.48
   700.2 1139.08   721.1 1138.00   749.1 1140.57   769.6 1139.60   791.0 1140.98
   832.9 1126.37   856.8 1121.47   888.7 1110.66   902.7 1110.42   910.0 1108.08
#Mann= 3 , 0 , 0
       0     0.1       0   447.5   0.045       0   462.5     0.1       0
Bank Sta=   447.5,   462.5
Exp/Cntr=0.3,0.1

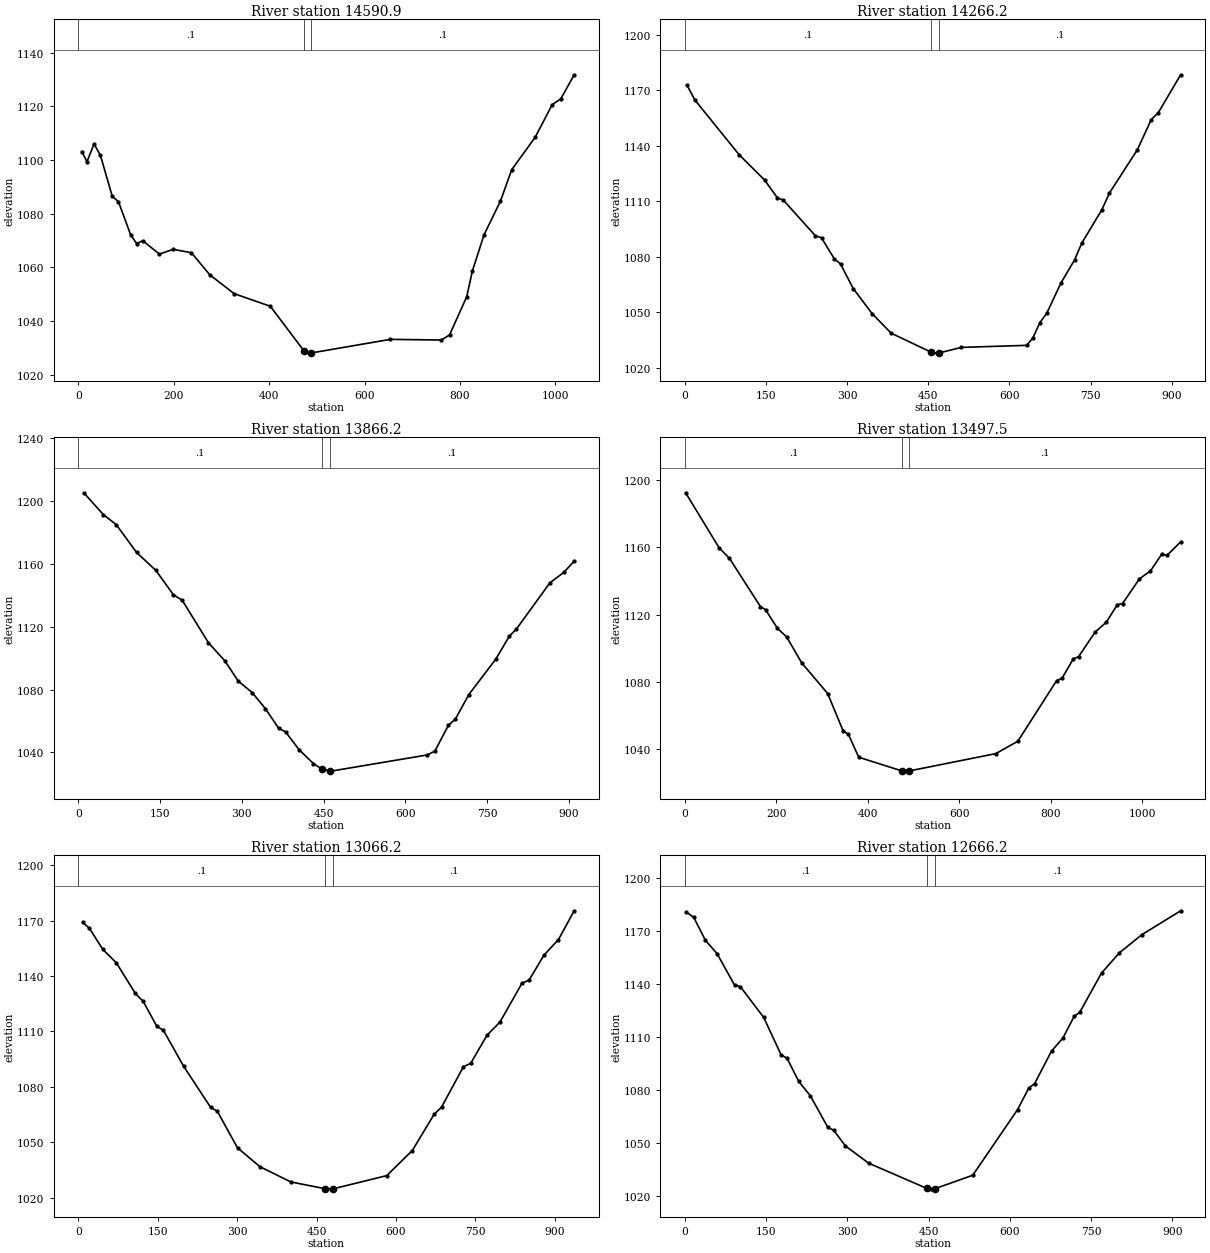
Type RM Length L Ch R = 1 ,14590.9,325.4,324.7,326.8
XS GIS Cut Line= 3
     1704279.733      386933.488     1704024.844      386624.827
     1703491.649      386272.717
#Sta/Elev= 30
     7.4 1103.16    18.1 1099.37    32.9 1106.01    46.4 1101.71    71.2 1086.43
    84.0 1084.54   109.5 1072.23   122.3 1068.87   135.0 1069.97   170.0 1064.94
   198.8 1066.76   237.1 1065.47   275.4 1057.28   326.5 1050.24   402.5 1045.53
   472.5 1029.03   484.0 1028.08   487.5 1028.12   654.1 1033.21   761.2 1032.96
   778.2 1034.88   814.2 1049.13   826.0 1058.73   850.5 1072.20   884.9 1084.74
   908.5 1096.44   957.7 1108.52   993.4 1120.68  1011.2 1122.76  1039.3 1131.75
#Mann= 3 , 0 , 0
       0     0.1       0   472.5   0.045       0   487.5     0.1       0
Bank Sta=   472.5,   487.5
Exp/Cntr=0.3,0.1

Type RM Length L Ch R = 1 ,14266.2,398,400,399.1
XS GIS Cut Line= 3
     1704442.975      386530.351     1704053.931      386279.973
     1703706.818      385987.893
#Sta/Elev= 30
     4.2 1172.57    18.6 1164.61   100.5 1135.01   147.3 1121.41   170.7 1111.90
   182.4 1110.40   241.0 1091.35   252.7 1090.08   276.1 1078.86   287.8 1075.97
   311.2 1062.72   346.3 1049.09   381.4 1038.57   455.2 1028.30   465.2 1027.79
   470.2 1027.92   511.1 1030.89   631.8 1032.00   643.4 1036.07   656.2 1044.30
   669.1 1049.45   694.8 1065.52   720.5 1078.29   733.4 1087.14   770.9 1105.39
   784.8 1114.34   836.3 1137.70   862.0 1154.05   874.9 1157.70   916.3 1178.22
#Mann= 3 , 0 , 0
       0     0.1       0   455.2   0.045       0   470.2     0.1       0
Bank Sta=   455.2,   470.2
Exp/Cntr=0.3,0.1

Type RM Length L Ch R = 1 ,13866.2,359.8,368.7,377.6
XS GIS Cut Line= 3
     1704649.516      386237.582     1704289.785      385958.981
     1703930.053      385680.380
#Sta/Elev= 30
    10.1 1205.35    46.0 1191.42    69.5 1185.12   106.8 1167.38   142.4 1155.86
   174.5 1140.39   190.6 1136.90   238.8 1109.82   268.6 1098.41   293.5 1085.38
   319.2 1078.03   343.3 1067.84   367.4 1055.42   380.6 1052.91   405.5 1041.50
   431.6 1032.77   447.5 1029.20   462.5 1028.02   463.8 1027.99   640.6 1038.31
   654.4 1040.78   679.3 1057.23   691.8 1061.04   716.7 1076.79   766.4 1099.47
   791.3 1114.16   803.8 1118.43   865.5 1148.02   890.9 1154.62   910.0 1161.75
#Mann= 3 , 0 , 0
       0     0.1       0   447.5   0.045       0   462.5     0.1       0
Bank Sta=   447.5,   462.5
Exp/Cntr=0.3,0.1

Type RM Length L Ch R = 1 ,13497.5,434.7,431.3,425.6
XS GIS Cut Line= 3
     1704763.213      386117.338     1704472.527      385603.708
     1704185.809      385201.296
#Sta/Elev= 30
     1.8 1192.45    75.1 1159.75    97.7 1153.47   165.5 1124.78   176.8 1122.94
   202.5 1111.89   222.5 1106.86   256.0 1091.24   312.5 1073.09   346.4 1050.82
   357.7 1048.92   380.4 1035.24   475.1 1027.09   482.0 1026.99   490.1 1027.06
   680.1 1037.40   728.4 1044.79   813.0 1080.76   825.1 1082.26   849.2 1093.55
   861.3 1095.12   897.6 1109.76   921.7 1115.47   945.9 1125.97   957.3 1126.63
   994.2 1141.29  1018.4 1146.04  1042.6 1155.82  1054.6 1155.28  1084.3 1163.26
#Mann= 3 , 0 , 0
       0     0.1       0   475.1   0.045       0   490.1     0.1       0
Bank Sta=   475.1,   490.1
Exp/Cntr=0.3,0.1

Type RM Length L Ch R = 1 ,13066.2,394.4,400,409.7
XS GIS Cut Line= 3
     1705192.457      385891.067     1704892.266      385524.293
     1704567.728      385194.382
#Sta/Elev= 30
     8.2 1169.04    20.9 1165.83    46.3 1154.36    71.8 1147.19   107.7 1130.56
   122.6 1126.25   148.1 1112.89   160.8 1110.57   198.9 1091.19   249.8 1068.96
   262.5 1066.83   300.7 1047.04   343.1 1036.83   401.4 1028.58   466.5 1024.89
   477.5 1024.69   481.5 1024.86   582.7 1032.01   630.9 1045.57   672.3 1065.22
   686.1 1069.02   727.5 1090.91   741.3 1092.77   772.1 1107.98   796.6 1115.12
   838.0 1136.04   851.8 1137.87   879.4 1151.20   907.0 1159.72   936.7 1175.28
#Mann= 3 , 0 , 0
       0     0.1       0   466.5   0.045       0   481.5     0.1       0
Bank Sta=   466.5,   481.5
Exp/Cntr=0.3,0.1

Type RM Length L Ch R = 1 ,12666.2,403.6,400,390.8
XS GIS Cut Line= 3
     1705424.858      385811.226     1705240.963      385395.817
     1705087.018      384961.437
#Sta/Elev= 30
     3.0 1180.79    16.5 1177.82    38.0 1164.82    59.5 1157.30    91.8 1139.45
   102.6 1138.55   145.6 1121.15   177.9 1099.85   188.7 1098.07   210.2 1084.91
   231.7 1076.75   264.0 1058.86   274.7 1057.28   296.3 1048.38   339.3 1038.60
   446.8 1024.28   454.3 1023.89   461.8 1024.16   531.4 1031.75   614.2 1068.95
   635.1 1081.29   645.5 1083.57   676.8 1102.09   697.7 1109.38   718.6 1121.72
   729.0 1124.08   769.1 1146.29   802.1 1157.76   843.8 1168.06   915.1 1181.52
#Mann= 3 , 0 , 0
       0     0.1       0   446.8   0.045       0   461.8     0.1       0
Bank Sta=   446.8,   461.8
Exp/Cntr=0.3,0.1

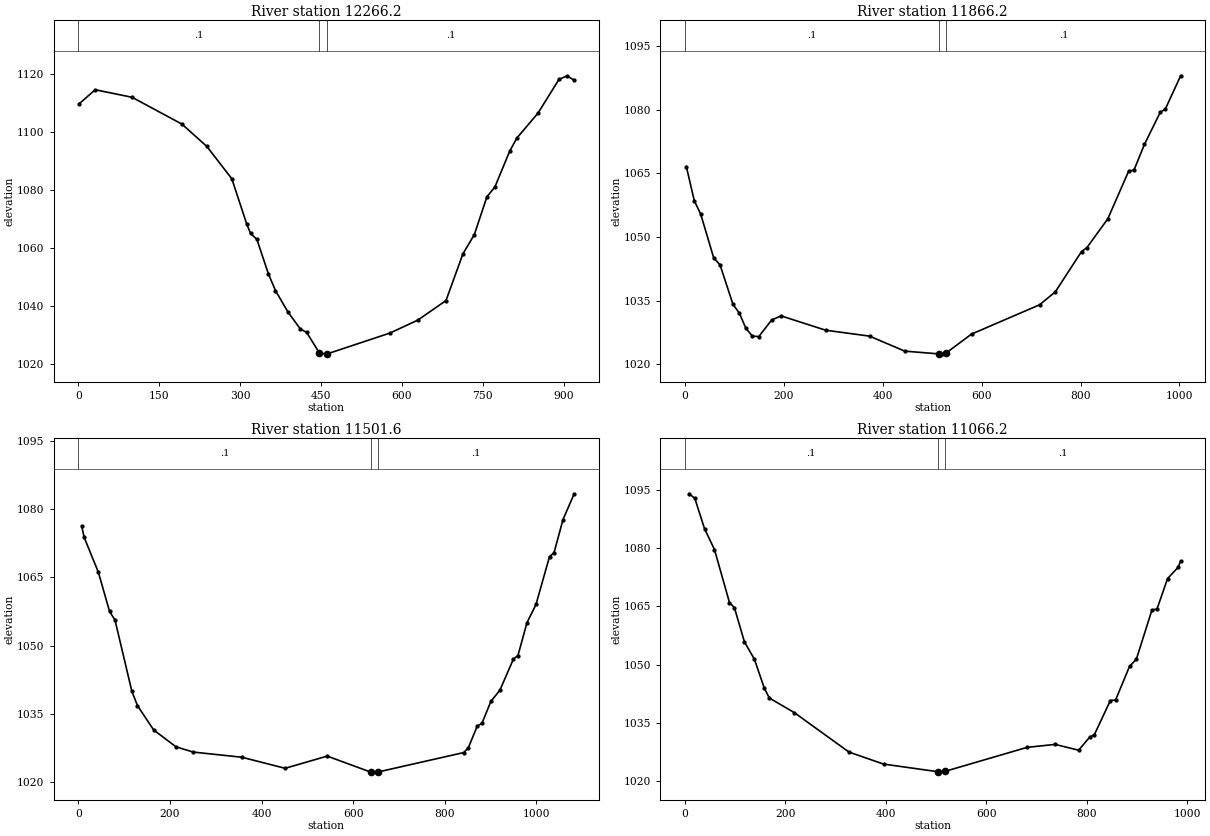
Type RM Length L Ch R = 1 ,12266.2,405.9,400,388.7
XS GIS Cut Line= 3
     1705821.367      385605.534     1705582.932      385219.081
     1705274.659      384870.164
#Sta/Elev= 30
     2.1 1109.93    31.3 1114.69    99.7 1112.08   192.2 1102.82   238.5 1095.10
   284.7 1083.96   312.4 1068.30   319.4 1065.13   331.2 1063.04   352.5 1051.16
   365.7 1045.35   388.8 1037.98   411.9 1032.08   423.5 1030.94   446.6 1023.97
   458.7 1023.43   461.6 1023.51   578.1 1030.71   629.4 1035.14   681.9 1041.90
   713.3    1058   734.5 1064.67   757.9 1077.75   772.7 1081.14   800.1 1093.47
   813.3 1097.99   852.6 1106.61   891.6 1118.26   906.5 1119.49   919.7 1117.98
#Mann= 3 , 0 , 0
       0     0.1       0   446.6   0.045       0   461.6     0.1       0
Bank Sta=   446.6,   461.6
Exp/Cntr=0.3,0.1

Type RM Length L Ch R = 1 ,11866.2,347.1,364.6,391.8
XS GIS Cut Line= 3
     1706183.493      385323.535     1705790.218      384981.982
     1705343.479      384802.533
#Sta/Elev= 30
     3.1 1066.62    19.2 1058.54    32.2 1055.38    58.3 1045.11    71.3 1043.39
    97.4 1034.08   110.4 1031.99   123.5 1028.43   136.5 1026.60   149.6 1026.48
   175.6 1030.40   194.6 1031.37   284.7 1027.99   373.4 1026.59   444.8 1023.04
   513.4 1022.40   519.2 1022.34   528.4 1022.62   579.6 1027.07   717.1 1033.98
   748.9 1037.03   802.0 1046.56   812.6 1047.45   855.0 1054.26   897.3 1065.56
   908.0 1065.78   929.2 1071.87   961.0 1079.40   971.6 1080.25  1002.3 1088.04
#Mann= 3 , 0 , 0
       0     0.1       0   513.4   0.045       0   528.4     0.1       0
Bank Sta=   513.4,   528.4
Exp/Cntr=0.3,0.1

Type RM Length L Ch R = 1 ,11501.6,438.4,435.4,424.8
XS GIS Cut Line= 3
     1706235.572      385270.698     1705906.119      384819.005
     1705911.149      384295.870
#Sta/Elev= 30
     7.3 1076.30    12.8 1073.78    43.8 1066.13    68.2 1057.53    80.0 1055.66
   116.9 1039.98   129.1 1036.86   164.5 1031.52   213.2 1027.82   250.9 1026.67
   356.8 1025.54   451.4 1023.11   543.2 1025.79   638.3 1022.27   639.5 1022.27
   654.5 1022.31   841.4 1026.57   851.3 1027.64   870.9 1032.42   880.8 1032.95
   900.5 1037.81   920.1 1040.25   949.7 1047.11   959.5 1047.86   979.2 1055.07
   998.9 1059.07  1028.4 1069.58  1038.2 1070.42  1057.9 1077.72  1082.2 1083.36
#Mann= 3 , 0 , 0
       0     0.1       0   639.5   0.045       0   654.5     0.1       0
Bank Sta=   639.5,   654.5
Exp/Cntr=0.3,0.1

Type RM Length L Ch R = 1 ,11066.2,405.4,400,401.3
XS GIS Cut Line= 3
     1706318.678      385254.582     1706253.549      384748.134
     1706104.683      384295.531
#Sta/Elev= 30
     8.5 1094.10    19.9 1092.96    39.3 1085.09    59.1 1079.70    88.9 1066.03
    98.8 1064.68   118.7 1055.86   138.5 1051.40   158.4 1043.86   168.3 1041.36
   217.9 1037.60   327.0 1027.39   395.6 1024.30   503.1 1022.34   505.6 1022.22
   518.1 1022.42   681.5 1028.62   737.3 1029.38   784.1 1027.88   805.8 1031.23
   815.3 1031.87   847.2 1040.71   857.6 1040.85   885.4 1049.52   899.0 1051.39
   930.1 1064.14   940.0 1064.31   961.1 1072.22   981.9 1075.09   987.1 1076.71
#Mann= 3 , 0 , 0
       0     0.1       0   503.1   0.045       0   518.1     0.1       0
Bank Sta=   503.1,   518.1
Exp/Cntr=0.3,0.1