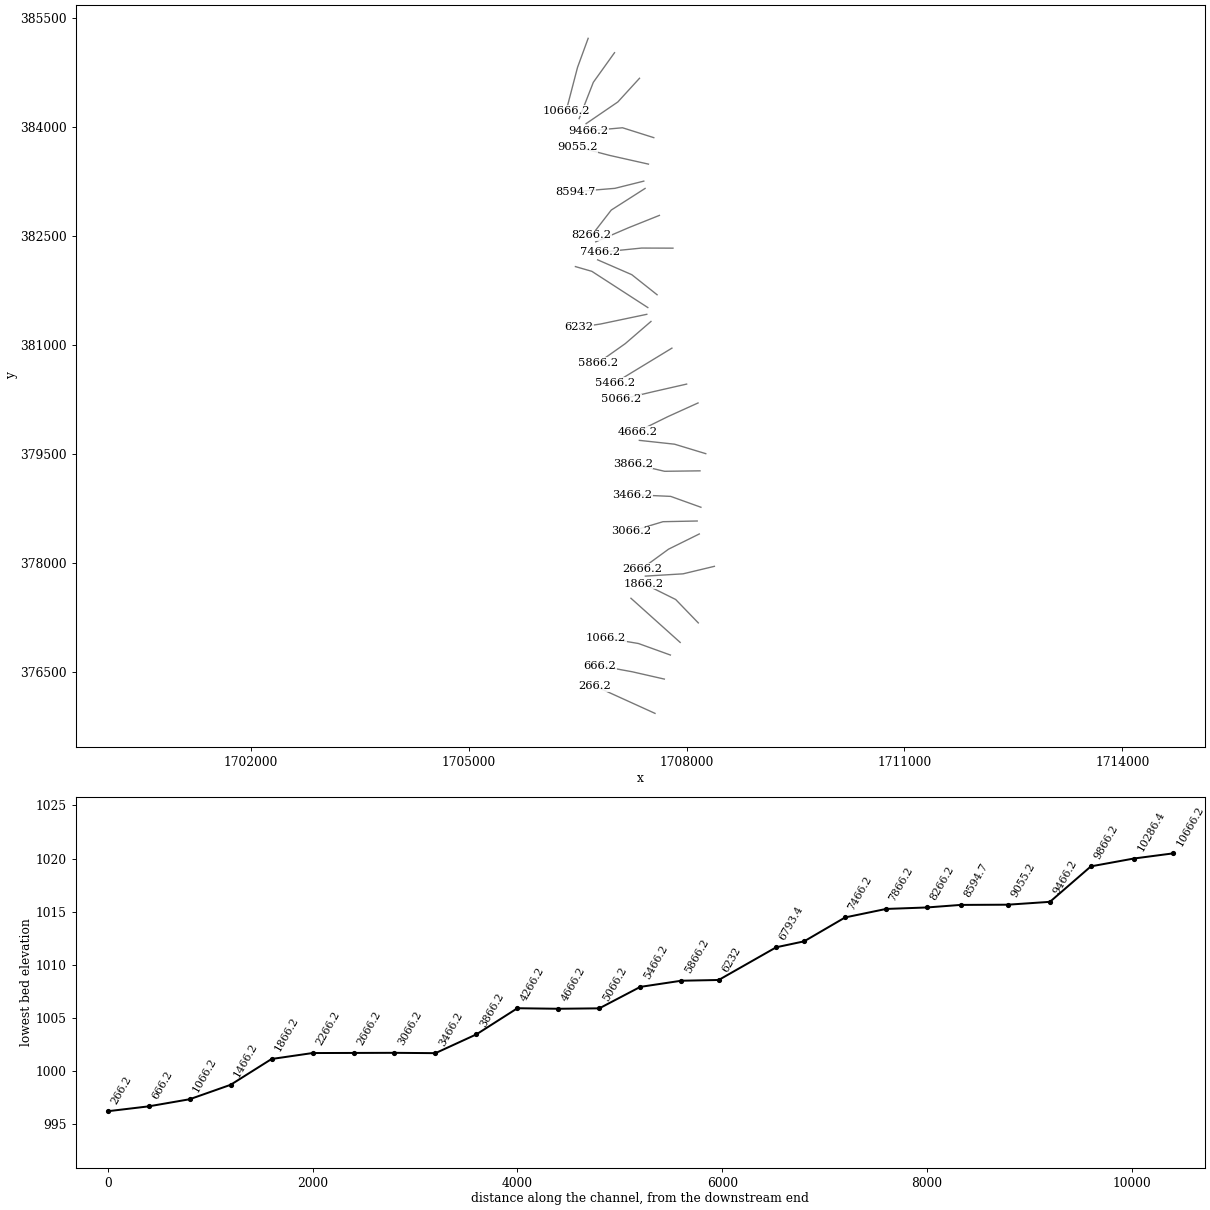
HEC-RAS study BrthlmwFrk.prj: BrthlmwFrk

--- BrthlmwFrk.g01 (geometry) --- (continued)

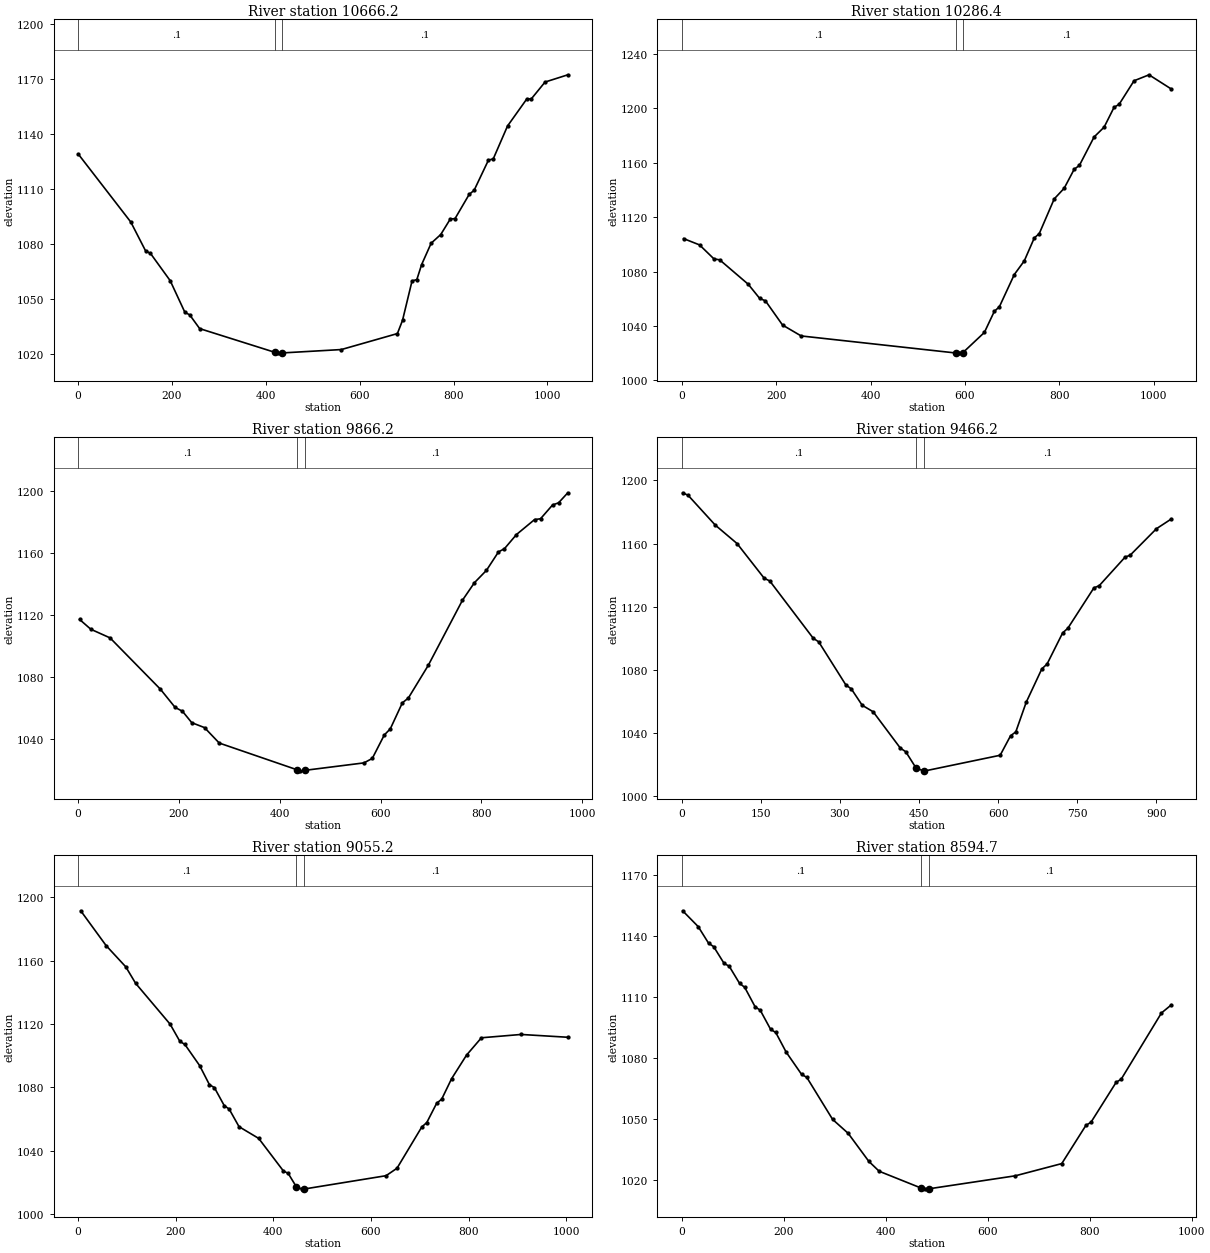
Type RM Length L Ch R = 1 ,10666.2,380.5,379.9,377.1
XS GIS Cut Line= 3
     1706644.721      385222.786     1706498.200      384822.317
     1706342.225      384225.473
#Sta/Elev= 30
     0.6 1129.07   112.4 1092.01   143.9 1076.28   154.3 1074.90   196.3 1060.02
   227.7 1042.70   237.7 1041.41   259.1 1033.86   418.9 1020.95   426.4 1020.48
   433.9 1020.57   560.9 1022.43   680.3 1031.15   691.2 1038.36   711.5 1059.89
   721.7 1060.61   731.9 1068.80   752.2 1080.45   772.6 1085.19   792.9 1093.63
   803.1 1093.90   833.3 1107.14   843.7 1109.31   874.3 1125.84   884.4 1126.43
   914.9 1144.42   955.6 1159.06   965.8 1159.30   994.8 1168.40  1043.2 1172.34
#Mann= 3 , 0 , 0
       0     0.1       0   418.9   0.045       0   433.9     0.1       0
Bank Sta=   418.9,   433.9
Exp/Cntr=0.3,0.1

Type RM Length L Ch R = 1 ,10286.4,428.4,420.1,406.6
XS GIS Cut Line= 3
     1707007.720      385025.241     1706715.972      384617.799
     1706520.723      384118.564
#Sta/Elev= 30
     4.0 1104.22    37.8 1099.59    68.4 1089.29    80.5 1088.61   141.0 1070.64
   165.3 1060.21   177.4 1058.46   213.7 1040.64   253.1 1032.63   580.8 1020.09
   588.3 1020.00   595.8 1020.43   641.1 1035.21   662.2 1050.75   672.8 1054.04
   704.5 1077.80   725.6 1087.83   746.8 1104.70   757.3 1107.88   789.0 1133.40
   810.1 1141.23   831.3 1155.22   842.3 1158.02   873.5 1178.96   894.7 1186.17
   915.8 1200.79   926.4 1202.93   958.1 1220.29   989.8 1224.65  1037.2 1214.16
#Mann= 3 , 0 , 0
       0     0.1       0   580.8   0.045       0   595.8     0.1       0
Bank Sta=   580.8,   595.8
Exp/Cntr=0.3,0.1

Type RM Length L Ch R = 1 ,9866.2,425.7,400,389.2
XS GIS Cut Line= 3
     1707351.880      384673.432     1707053.485      384347.484
     1706616.365      384049.199
#Sta/Elev= 30
     3.1 1117.02    25.4 1110.70    63.5 1105.14   163.4 1072.04   192.5 1060.34
   207.1 1057.84   225.5 1050.49   250.8 1047.31   280.0 1037.36   434.4 1020.12
   440.3 1019.26   449.4 1019.75   567.0 1024.57   583.5 1027.46   607.3 1042.56
   619.2 1046.51   643.1 1063.27   655.0 1066.38   694.4 1087.39   762.2 1129.37
   786.0 1140.70   809.9 1148.69   833.7 1160.56   845.6 1162.65   869.4 1171.76
   905.2 1181.38   917.1 1181.93   940.9 1190.80   952.8 1192.19   971.1 1198.64
#Mann= 3 , 0 , 0
       0     0.1       0   434.4   0.045       0   449.4     0.1       0
Bank Sta=   434.4,   449.4
Exp/Cntr=0.3,0.1

Type RM Length L Ch R = 1 ,9466.2,409.1,411.1,403.4
XS GIS Cut Line= 3
     1707548.340      383856.514     1707117.522      383992.539
     1706642.655      383949.759
#Sta/Elev= 30
     1.8 1192.19    12.1 1190.66    63.7 1171.75   105.0 1160.08   156.6 1138.05
   167.0 1136.39   249.5 1100.06   259.8 1097.83   311.4 1070.47   321.7 1068.00
   342.3 1057.64   363.1 1053.52   414.6 1030.51   424.9 1028.20   444.3 1017.95
   459.3 1015.92   603.9 1025.97   623.6 1038.31   633.5 1040.75   653.3 1059.55
   682.9 1080.69   692.8 1083.73   722.4 1103.47   732.3 1106.44   781.7 1132.02
   791.6 1133.33   841.0 1151.55   850.2 1152.61   900.3 1169.48   928.6 1175.67
#Mann= 3 , 0 , 0
       0     0.1       0   444.3   0.045       0   459.3     0.1       0
Bank Sta=   444.3,   459.3
Exp/Cntr=0.3,0.1

Type RM Length L Ch R = 1 ,9055.2,453.6,460.5,467.3
XS GIS Cut Line= 3
     1707474.761      383492.375     1706942.329      383611.770
     1706499.676      383727.463
#Sta/Elev= 30
     5.6 1191.37    57.5 1169.43    97.8 1156.01   118.0 1145.59   188.6 1119.82
   208.7 1108.91   218.8 1107.03   249.1 1093.66   269.2 1081.57   279.3 1079.76
   299.5 1068.38   309.6 1066.20   329.8 1055.08   370.1 1047.67   420.5 1027.19
   430.6 1025.54   447.4 1017.02   459.8 1015.65   462.4 1015.68   631.0 1024.13
   653.4 1028.84   704.2 1054.91   714.4 1057.69   734.7 1069.90   744.9 1072.43
   765.2 1085.36   795.8 1100.25   826.3 1111.21   907.6 1113.31  1003.2 1111.54
#Mann= 3 , 0 , 0
       0     0.1       0   447.4   0.045       0   462.4     0.1       0
Bank Sta=   447.4,   462.4
Exp/Cntr=0.3,0.1

Type RM Length L Ch R = 1 ,8594.7,323,328.5,347.1
XS GIS Cut Line= 3
     1707410.732      383258.286     1707012.751      383159.057
     1706464.465      383113.785
#Sta/Elev= 30
     2.0 1152.41    32.4 1144.66    52.7 1136.52    62.8 1134.79    83.1 1126.59
    93.2 1125.18   113.5 1116.76   123.6 1114.82   143.9 1105.29   154.1 1103.54
   174.4 1094.16   184.5 1092.62   204.8 1083.01   235.2 1072.01   245.3 1070.57
   296.0 1049.89   326.5 1043.05   367.0 1029.27   387.3 1024.41     469 1016.21
   476.8 1015.63     484 1015.76   654.5 1022.19   745.3 1028.18   792.7 1046.98
   802.6 1048.49   852.0 1068.15   861.8 1069.64   940.8 1102.21   960.3 1106.22
#Mann= 3 , 0 , 0
       0     0.1       0     469   0.045       0     484     0.1       0
Bank Sta=     469,     484
Exp/Cntr=0.3,0.1

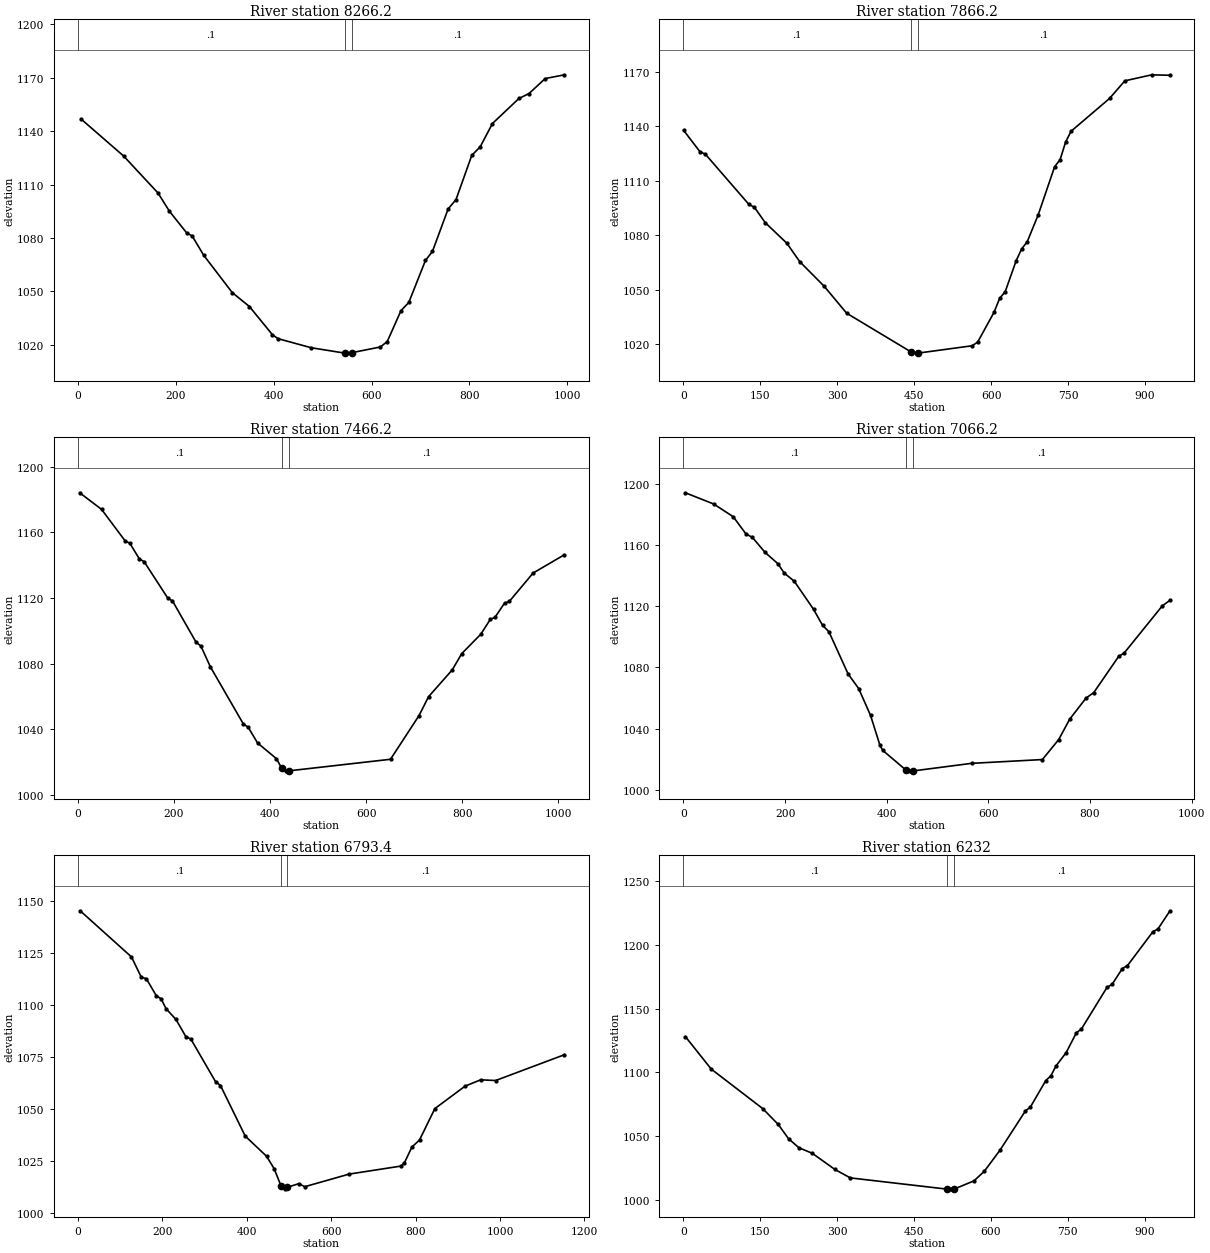
Type RM Length L Ch R = 1 ,8266.2,398.5,400,389.4
XS GIS Cut Line= 3
     1707428.627      383157.813     1706963.074      382860.444
     1706692.673      382511.545
#Sta/Elev= 30
     6.3 1146.88    93.5 1126.05   163.6 1105.34   186.9 1095.13   222.0 1082.99
   233.6 1081.14   257.0 1070.36   315.4 1049.38   350.4 1041.57   397.1 1025.84
   408.8 1023.52   476.6 1018.42   544.9 1015.41   546.1 1015.39   559.9 1015.66
   618.0 1018.85   632.0 1021.89   660.0 1039.18   676.1 1043.87   710.0 1067.40
   724.3 1072.46   756.4 1096.35   772.5 1101.62   804.6 1126.38   822.0 1131.27
   846.9 1144.31   901.0 1158.37   921.6 1161.12   954.7 1169.56   993.8 1171.65
#Mann= 3 , 0 , 0
       0     0.1       0   544.9   0.045       0   559.9     0.1       0
Bank Sta=   544.9,   559.9
Exp/Cntr=0.3,0.1

Type RM Length L Ch R = 1 ,7866.2,409,400,392.4
XS GIS Cut Line= 3
     1707625.638      382787.033     1707207.424      382619.992
     1706749.111      382423.389
#Sta/Elev= 30
     0.3 1137.79    32.1 1126.05    42.7 1124.68   127.5 1097.09   138.3 1095.47
   159.3 1087.06   201.7 1075.66   226.5 1065.64   274.3 1052.04   318.2 1037.20
   442.8 1016.07   455.8 1015.25   457.8 1015.27   563.1 1019.31   573.8 1021.39
   605.6 1037.74   616.6 1045.44   627.3 1049.03   648.8 1066.16   659.5 1072.62
   670.2 1076.47   691.6 1091.27   723.7 1117.77   734.4 1121.69   745.1 1131.34
   755.8 1137.31   830.8 1155.35   860.6 1165.04   913.0 1168.34   948.6 1168.09
#Mann= 3 , 0 , 0
       0     0.1       0   442.8   0.045       0   457.8     0.1       0
Bank Sta=   442.8,   457.8
Exp/Cntr=0.3,0.1

Type RM Length L Ch R = 1 ,7466.2,415,400,388.6
XS GIS Cut Line= 3
     1707812.388      382336.273     1707380.581      382337.571
     1706802.845      382279.238
#Sta/Elev= 30
     3.9 1184.02    49.3 1173.95    98.5 1154.69   108.3 1153.22   128.0 1143.74
   137.9 1142.09   187.1 1119.89   196.9 1118.18   246.1 1092.95   256.0 1090.71
   275.6 1078.10   344.5 1043.14   354.4 1041.23   374.0 1031.61   413.4 1022.01
   424.3 1016.18   433.1 1014.45   439.3 1014.63   650.7 1021.67   710.0 1048.29
   729.8 1059.77   779.2 1076.14   799.0 1086.07   838.6 1097.86   858.3 1106.89
   868.2 1108.19   888.0 1116.79   897.9 1117.83   947.4 1135.13  1012.5 1146.28
#Mann= 3 , 0 , 0
       0     0.1       0   424.3   0.045       0   439.3     0.1       0
Bank Sta=   424.3,   439.3
Exp/Cntr=0.3,0.1

Type RM Length L Ch R = 1 ,7066.2,270.6,272.8,268.9
XS GIS Cut Line= 3
     1707593.822      381695.306     1707245.037      381971.630
     1706775.135      382175.722
#Sta/Elev= 30
     3.9 1194.26    59.5 1186.95    97.9 1178.63   122.9 1167.39   135.6 1165.09
   160.7 1155.25   185.8 1147.90   198.3 1141.72   217.9 1136.49   256.0 1118.03
   273.7 1107.57   286.2 1103.39   323.9 1075.80   344.7 1066.25   368.1 1048.66
   386.6 1029.13   392.2 1025.74   437.5 1012.99   445.0 1012.20   452.5 1012.35
   566.8 1017.29   706.2 1019.77   738.4 1032.86   759.9 1046.13   792.1 1059.98
   807.4 1063.60   856.4 1087.25   867.2 1089.46   942.3 1120.34   957.3 1123.95
#Mann= 3 , 0 , 0
       0     0.1       0   437.5   0.045       0   452.5     0.1       0
Bank Sta=   437.5,   452.5
Exp/Cntr=0.3,0.1

Type RM Length L Ch R = 1 ,6793.4,544.4,561.4,578.8
XS GIS Cut Line= 3
     1707466.253      381519.043     1706695.851      382017.213
     1706469.495      382082.605
#Sta/Elev= 30
     5.6 1145.30   127.0 1123.16   150.4 1113.34   162.1 1112.74   185.6 1104.59
   197.3 1103.01   209.0 1098.28   232.4 1093.14   255.9 1084.84   267.6 1083.74
   326.2 1063.24   337.9 1061.37   396.5 1037.11   447.0 1027.43   465.1 1021.42
   481.4 1013.11   490.2 1011.64   496.4 1012.56   523.1 1014.24   537.6 1012.81
   642.6 1018.86   765.0 1022.70   773.2 1024.06   791.3 1031.86   809.4 1035.24
   845.7 1050.31   917.4 1061.11   954.3 1064.14   989.7 1063.80  1152.5 1076.18
#Mann= 3 , 0 , 0
       0     0.1       0   481.4   0.045       0   496.4     0.1       0
Bank Sta=   481.4,   496.4
Exp/Cntr=0.3,0.1

Type RM Length L Ch R = 1 ,6232,353.6,365.8,375.4
XS GIS Cut Line= 3
     1707452.063      381426.020     1706816.575      381292.873
     1706519.796      381247.601
#Sta/Elev= 30
     3.9 1127.93    54.2 1102.58   154.8 1071.60   184.9 1059.24   205.0 1048.08
   225.1 1041.03   251.6 1036.58   295.5 1023.96   325.7 1017.35   513.7 1008.59
   522.1 1008.56   528.7 1008.70   567.0 1015.03   587.1 1022.52   617.4 1038.84
   667.3 1069.75   677.3 1072.98   707.1 1093.58   717.1 1097.31   727.0 1105.00
   746.9 1115.48   766.8 1130.98   776.8 1134.04   826.6 1166.58   836.5 1168.91
   856.4 1181.25   866.6 1183.67   916.2 1210.17   926.1 1212.36   949.5 1226.54
#Mann= 3 , 0 , 0
       0     0.1       0   513.7   0.045       0   528.7     0.1       0
Bank Sta=   513.7,   528.7
Exp/Cntr=0.3,0.1

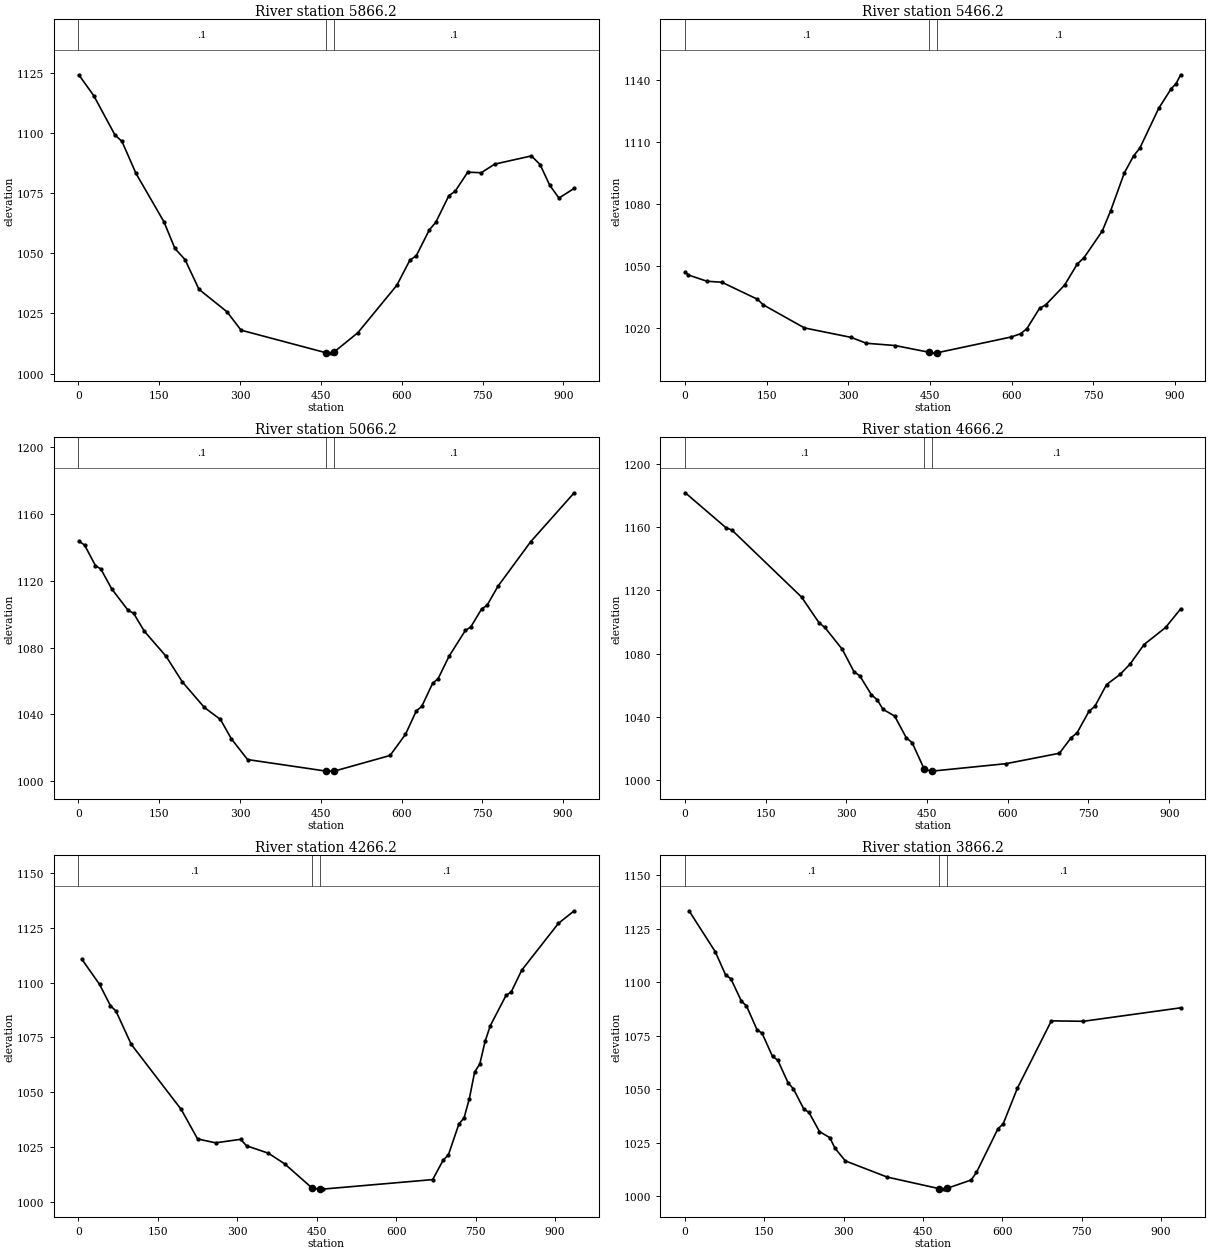
Type RM Length L Ch R = 1 ,5866.2,403.7,400,398.5
XS GIS Cut Line= 3
     1707509.480      381327.776     1707155.837      381022.815
     1706785.916      380761.538
#Sta/Elev= 30
     0.9 1124.05    28.6 1115.40    67.9 1099.09    80.9 1096.41   106.9 1083.14
   158.9 1063.00   179.2 1051.94   197.9 1047.34   223.8 1034.99   275.8 1025.65
   301.8 1018.03   459.5 1008.64   468.3 1008.49   474.5 1008.97   518.6 1016.96
   590.9 1036.66   615.0 1047.03   627.1 1048.99   651.2 1059.66   663.2 1062.83
   687.3 1073.80   699.3 1075.77   722.5 1083.64   747.5 1083.39   772.3 1086.96
   840.6 1090.38   856.6 1086.81   874.7 1078.16   891.7 1072.88   919.9 1076.89
#Mann= 3 , 0 , 0
       0     0.1       0   459.5   0.045       0   474.5     0.1       0
Bank Sta=   459.5,   474.5
Exp/Cntr=0.3,0.1

Type RM Length L Ch R = 1 ,5466.2,407.3,400,392.9
XS GIS Cut Line= 3
     1707797.857      380960.632     1707409.048      380724.301
     1707020.239      380487.969
#Sta/Elev= 30
     0.9 1047.25     6.2 1045.80    40.7 1042.73    67.9 1042.26   132.8 1034.08
   144.1 1031.29   219.5 1020.13   305.5 1015.52   333.1 1012.70   386.2 1011.58
   447.5 1008.37   459.2 1007.91   462.5 1008.05   598.4 1015.69   616.5 1017.31
   628.0 1019.83   651.0 1029.58   662.5 1031.31   697.1 1040.89   720.1 1051.01
   732.6 1054.12   766.2 1067.06   781.5 1076.83   806.7 1095.23   823.7 1103.45
   835.2 1107.26   869.8 1126.50   892.8 1136.07   901.5 1138.40   910.0 1142.74
#Mann= 3 , 0 , 0
       0     0.1       0   447.5   0.045       0   462.5     0.1       0
Bank Sta=   447.5,   462.5
Exp/Cntr=0.3,0.1

Type RM Length L Ch R = 1 ,5066.2,395.4,400,405.1
XS GIS Cut Line= 3
     1708000.594      380466.106     1707544.640      380362.356
     1707104.030      380258.107
#Sta/Elev= 30
     1.4 1143.70    11.5 1141.53    31.7 1129.16    41.8 1127.09    61.9 1115.23
    92.2 1102.40   102.6 1100.55   122.5 1089.80   162.9 1074.75   193.1 1059.38
   234.0 1044.06   263.8 1036.89   284.0 1025.27   314.2 1012.82   460.1 1005.89
   475.1 1005.89   578.7 1015.28   607.2 1027.90   627.4 1042.01   637.5 1044.71
   657.7 1058.56   667.8 1061.30   688.1 1074.74   718.4 1090.24   728.5 1092.34
   748.7 1103.20   758.6 1105.25   779.1 1116.85   839.7 1143.47   920.4 1172.80
#Mann= 3 , 0 , 0
       0     0.1       0   460.1   0.045       0   475.1     0.1       0
Bank Sta=   460.1,   475.1
Exp/Cntr=0.3,0.1

Type RM Length L Ch R = 1 ,4666.2,416.3,400,387.3
XS GIS Cut Line= 3
     1708157.549      380206.557     1707745.538      380019.877
     1707324.843      379812.976
#Sta/Elev= 30
     1.0 1181.65    76.6 1159.59    87.4 1158.17   217.0 1115.78   249.4 1099.55
   260.2 1096.62   292.6 1082.81   314.2 1068.71   325.0 1066.09   346.6 1054.16
   357.5 1050.88   368.3 1044.88   389.9 1040.63   411.5 1026.89   422.3 1023.87
   444.8 1007.16   457.5 1005.85   459.8 1005.86   597.3 1010.58   696.0 1017.14
   717.9 1026.99   728.9 1030.08   750.8 1043.59   761.8 1046.77   783.7 1060.56
   808.6 1066.90   827.5 1073.58   853.2 1085.79   893.3 1096.60   921.2 1108.32
#Mann= 3 , 0 , 0
       0     0.1       0   444.8   0.045       0   459.8     0.1       0
Bank Sta=   444.8,   459.8
Exp/Cntr=0.3,0.1

Type RM Length L Ch R = 1 ,4266.2,392.9,400,397.2
XS GIS Cut Line= 3
     1708263.937      379508.942     1707834.082      379639.337
     1707349.530      379691.844
#Sta/Elev= 30
     6.7 1110.61    40.1 1099.16    60.7 1089.43    71.0 1087.06    99.8 1071.91
   194.3 1042.19   225.2 1028.77   259.1 1026.99   306.5 1028.59   317.7 1025.63
   358.9 1022.26   389.7 1017.40   441.7 1006.33   456.7 1005.92   461.2 1005.90
   669.1 1010.24   688.9 1019.07   698.8 1021.50   718.6 1035.53   728.5 1038.39
   738.4 1047.16   748.3 1059.15   758.2 1062.99   768.1 1073.20   778.0 1080.39
   807.6 1094.11   817.5 1095.75   837.3 1105.64   906.6 1126.97   936.3 1132.68
#Mann= 3 , 0 , 0
       0     0.1       0   441.7   0.045       0   456.7     0.1       0
Bank Sta=   441.7,   456.7
Exp/Cntr=0.3,0.1

Type RM Length L Ch R = 1 ,3866.2,408.2,400,404.3
XS GIS Cut Line= 3
     1708184.704      379272.620     1707696.975      379266.418
     1707259.395      379368.269
#Sta/Elev= 30
     8.1 1133.40    57.6 1114.28    77.2 1103.40    87.1 1101.69   106.8 1091.30
   116.6 1088.98   136.3 1077.98   146.1 1076.19   165.8 1065.38   175.6 1063.70
   195.3 1053.02   205.2 1050.30   224.8 1040.87   234.7 1039.25   254.4 1030.35
   274.0 1027.49   283.9 1022.50   303.6 1016.60   382.3 1009.08   480.3 1003.68
   490.6 1003.44   495.3 1003.78   541.1 1007.70   551.2 1011.25   591.6 1031.54
   601.7 1033.93   628.5 1050.56   692.7 1082.01   753.3 1081.82   937.0 1088.10
#Mann= 3 , 0 , 0
       0     0.1       0   480.3   0.045       0   495.3     0.1       0
Bank Sta=   480.3,   495.3
Exp/Cntr=0.3,0.1

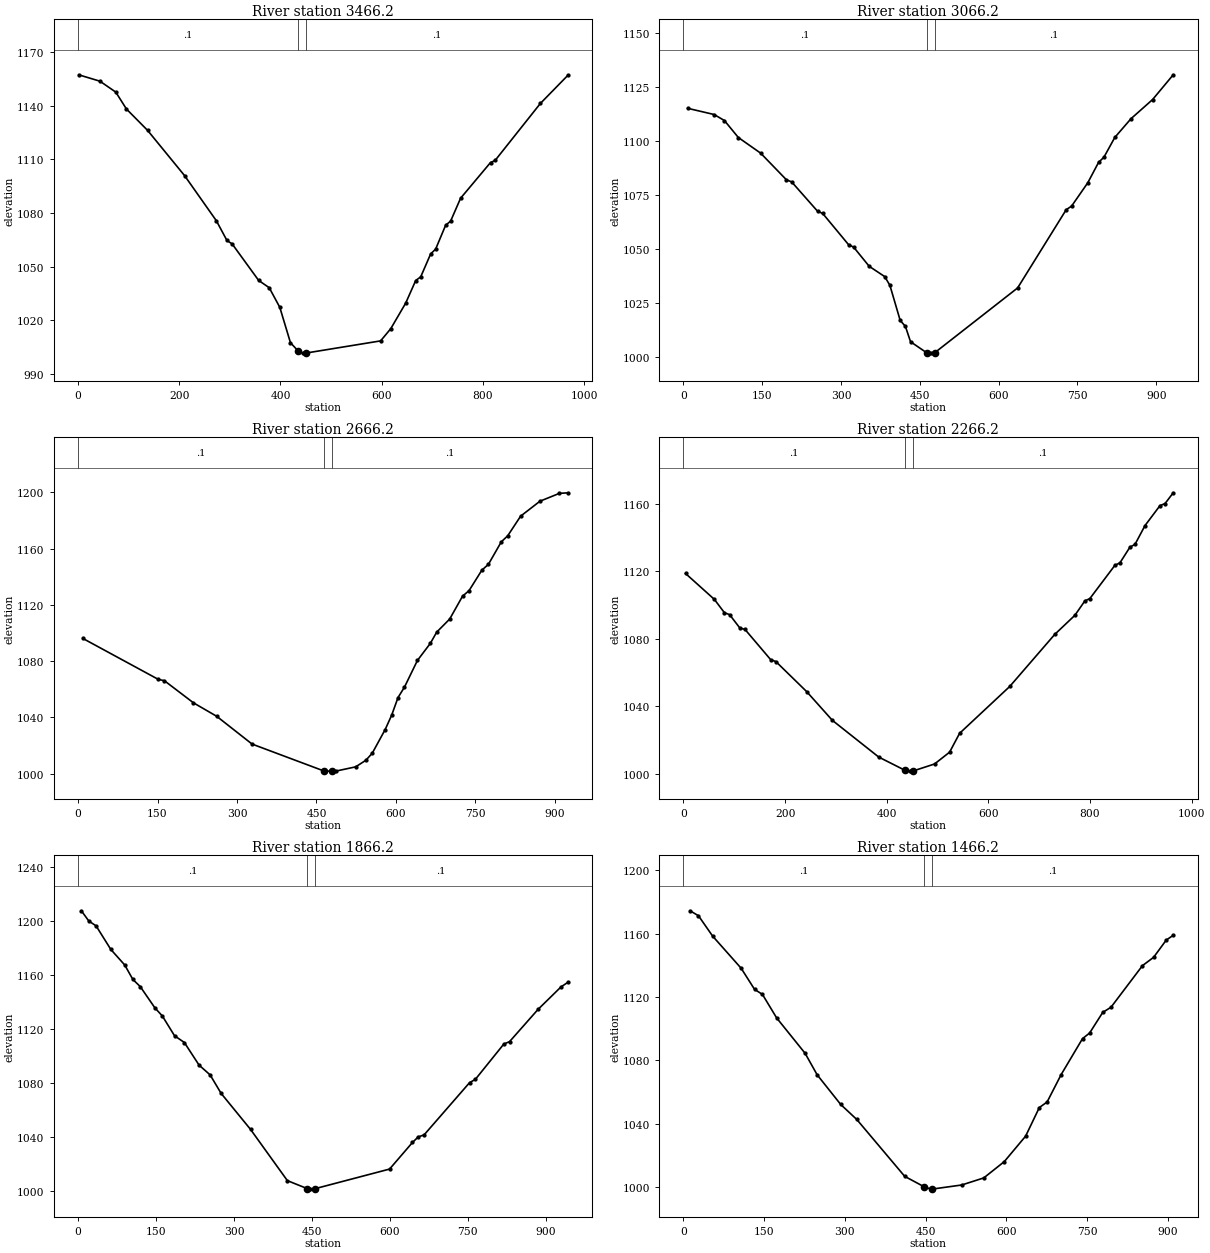
Type RM Length L Ch R = 1 ,3466.2,392,400,407.7
XS GIS Cut Line= 3
     1708197.410      378771.681     1707780.817      378921.241
     1707256.230      378944.869
#Sta/Elev= 30
     1.5 1157.16    43.3 1153.60    74.6 1147.50    95.6 1138.08   137.4 1126.14
   210.6 1100.82   273.3 1075.64   294.2 1064.63   304.6 1062.66   356.9 1042.29
   377.8 1038.21   398.7 1027.25   419.7 1007.51   435.1 1002.83   444.0 1001.67
   450.1 1001.70   597.9 1008.51   618.0 1015.36   647.5 1029.65   667.2 1042.23
   677.1 1044.28   696.8 1057.12   706.6 1059.78   726.3 1073.10   736.2 1075.43
   755.9 1088.22   815.0 1108.15   824.1 1109.32   913.5 1141.15   967.7 1156.83
#Mann= 3 , 0 , 0
       0     0.1       0   435.1   0.045       0   450.1     0.1       0
Bank Sta=   435.1,   450.1
Exp/Cntr=0.3,0.1

Type RM Length L Ch R = 1 ,3066.2,389.6,400,407.7
XS GIS Cut Line= 3
     1708146.123      378582.513     1707675.309      378573.114
     1707233.481      378440.340
#Sta/Elev= 30
     8.0 1115.29    58.3 1112.41    78.0 1109.61   104.5 1101.74   146.9 1094.49
   196.1 1082.10   206.0 1081.15   255.2 1067.56   265.0 1066.52   314.2 1052.05
   324.1 1050.84   353.6 1041.98   383.1 1037.21   393.0 1033.16   412.6 1016.87
   422.5 1014.13   432.3 1006.98   463.4 1001.81   470.9 1001.70   478.4 1001.90
   636.1 1031.94   728.6 1068.24   738.9 1069.92   769.7 1080.74   790.2 1090.18
   800.5 1092.62   821.1 1101.76   851.9 1110.45   893.0 1119.33   932.3 1130.82
#Mann= 3 , 0 , 0
       0     0.1       0   463.4   0.045       0   478.4     0.1       0
Bank Sta=   463.4,   478.4
Exp/Cntr=0.3,0.1

Type RM Length L Ch R = 1 ,2666.2,405,400,387.1
XS GIS Cut Line= 3
     1708174.834      378404.325     1707751.580      378195.068
     1707386.112      377928.678
#Sta/Elev= 30
     9.3 1096.05   151.6 1066.95   163.0 1066.02   217.8 1050.30   261.7 1040.71
   328.5 1020.94   464.7 1001.71   479.7 1001.70   486.4 1001.69   524.0 1004.73
   543.2 1009.39   555.3 1014.41   579.7 1031.25   591.9 1041.41   604.0 1054.04
   616.2 1061.50   640.6 1080.44   664.9 1092.54   677.1 1100.64   701.5 1109.88
   725.8 1126.18   738.0 1130.08   762.3 1144.71   774.5 1148.76   798.9 1164.81
   811.0 1169.11   835.4 1183.09   871.9 1193.73   908.5 1199.30   924.4 1199.69
#Mann= 3 , 0 , 0
       0     0.1       0   464.7   0.045       0   479.7     0.1       0
Bank Sta=   464.7,   479.7
Exp/Cntr=0.3,0.1

Type RM Length L Ch R = 1 ,2266.2,423.4,400,388.6
XS GIS Cut Line= 3
     1708382.733      377958.900     1707951.391      377855.775
     1707432.162      377824.438
#Sta/Elev= 30
     4.1 1118.72    60.9 1103.36    80.7 1095.46    90.8 1094.35   111.0 1086.43
   121.1 1085.60   171.7 1067.67   181.8 1066.58   242.5 1048.76   293.1 1031.73
   384.2 1010.02     436 1002.15   444.9 1001.68     451 1001.68   494.1 1005.91
   523.7 1012.90   543.4 1024.07   642.0 1051.80   730.7 1082.67   770.2 1093.94
   789.9 1102.49   799.7 1103.86   849.0 1123.56   858.9 1125.02   878.6 1134.32
   888.5 1135.94   908.2 1147.08   937.7 1158.91   947.6 1160.11   963.7 1166.48
#Mann= 3 , 0 , 0
       0     0.1       0     436   0.045       0     451     0.1       0
Bank Sta=     436,     451
Exp/Cntr=0.3,0.1

Type RM Length L Ch R = 1 ,1866.2,398.4,400,393.6
XS GIS Cut Line= 3
     1708161.169      377180.607     1707849.660      377502.695
     1707406.926      377722.281
#Sta/Elev= 30
     6.5 1207.68    20.6 1200.19    34.8 1196.48    63.1 1179.02    89.9 1167.45
   105.5 1156.76   119.7 1151.45   148.0 1135.60   162.2 1129.64   185.7 1114.94
   204.6 1109.94   232.9 1093.15   254.1 1085.93   275.4 1072.14   332.0 1045.41
   402.8 1007.42   440.6 1001.57   445.8 1001.12   455.6 1001.41   599.4 1016.00
   643.5 1035.76   654.6 1039.91   665.8 1041.36   753.4 1080.17   764.4 1082.56
   819.3 1108.83   830.3 1110.60   885.2 1134.57   929.2 1151.19   942.3 1154.57
#Mann= 3 , 0 , 0
       0     0.1       0   440.6   0.045       0   455.6     0.1       0
Bank Sta=   440.6,   455.6
Exp/Cntr=0.3,0.1

Type RM Length L Ch R = 1 ,1466.2,391.4,400,412.7
XS GIS Cut Line= 3
     1707911.789      376912.114     1707572.977      377215.810
     1707234.165      377519.507
#Sta/Elev= 30
    12.5 1174.35    27.9 1171.24    54.3 1158.37   107.2 1138.11   132.1 1124.79
   146.8 1121.58   173.3 1106.69   226.1 1084.40   248.4 1070.86   292.2 1052.13
   322.1 1042.64   411.1 1006.76   447.5 1000.13   459.7  998.69   462.5  998.73
   516.9 1001.29   558.0 1005.76   596.1 1016.04   635.8 1032.14   661.2 1050.15
   675.7 1053.69   701.9 1071.04   741.5 1093.68   754.7 1097.22   779.1 1110.25
   794.4 1113.48   852.9 1139.76   873.6 1145.00   897.1 1155.90   910.0 1158.88
#Mann= 3 , 0 , 0
       0     0.1       0   447.5   0.045       0   462.5     0.1       0
Bank Sta=   447.5,   462.5
Exp/Cntr=0.3,0.1

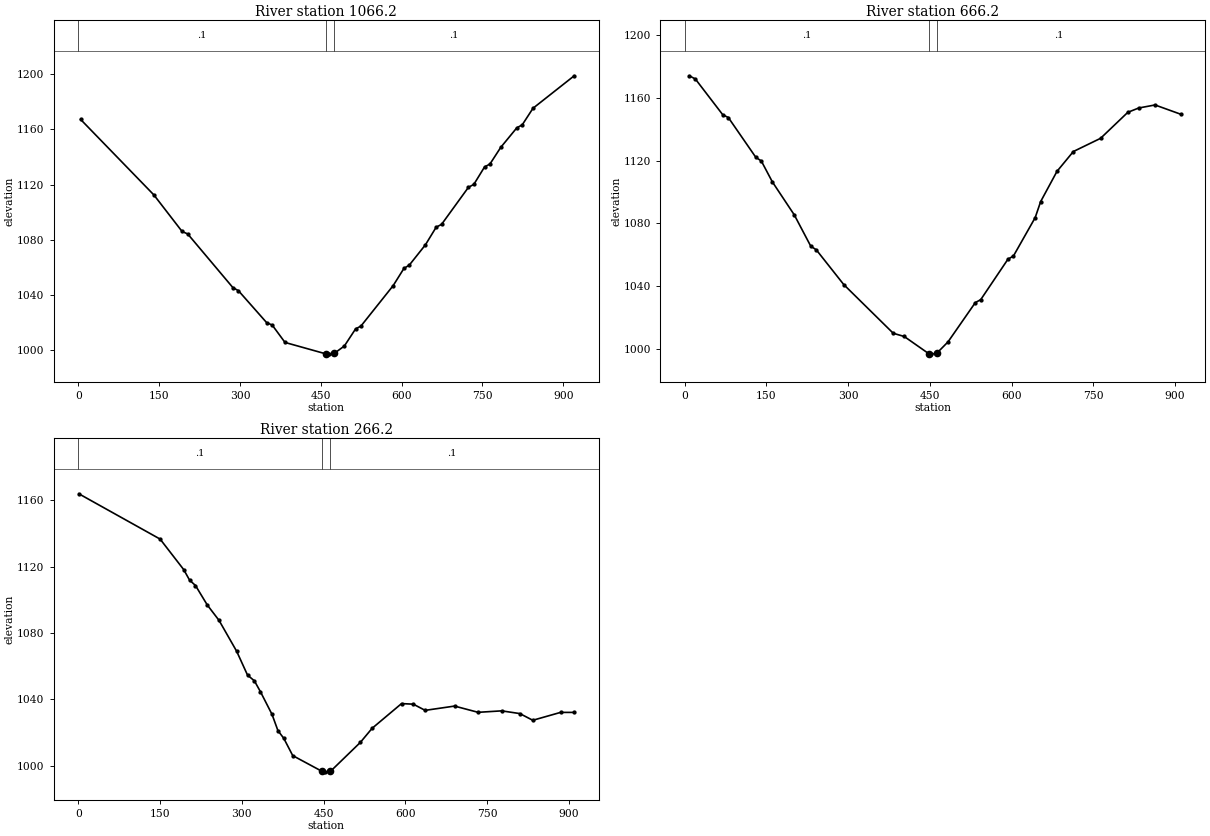
Type RM Length L Ch R = 1 ,1066.2,397.2,400,399.7
XS GIS Cut Line= 3
     1707776.957      376738.637     1707337.162      376897.171
     1706890.675      376972.451
#Sta/Elev= 30
     4.3 1167.21   140.3 1112.54   192.6 1086.11   203.0 1084.34   286.7 1045.55
   297.2 1043.23   349.5 1020.14   359.9 1018.35   383.6 1005.79     460  997.46
   464.5  997.33     475  997.86   493.8 1003.22   514.6 1015.60   524.5 1017.62
   584.4 1046.94   604.4 1059.41   614.3 1061.76   644.3 1076.49   664.2 1089.23
   674.2 1091.26   724.1 1118.10   734.1 1120.20   754.0 1132.85   764.0 1134.94
   784.0 1146.98   813.9 1161.17   823.9 1163.29   843.9 1175.30   920.3 1198.79
#Mann= 3 , 0 , 0
       0     0.1       0     460   0.045       0     475     0.1       0
Bank Sta=     460,     475
Exp/Cntr=0.3,0.1

Type RM Length L Ch R = 1 ,666.2,404.6,400,394.4
XS GIS Cut Line= 3
     1707693.424      376407.769     1707249.256      376508.805
     1706801.741      376590.490
#Sta/Elev= 30
     8.4 1174.02    19.4 1172.00    69.8 1149.17    79.9 1147.46   130.4 1122.08
   140.5 1119.75   160.7 1106.47   201.0 1085.41   231.3 1065.44   241.4 1063.15
   291.9 1040.98   382.7 1009.96   402.9 1007.90     448  996.94   452.4  996.66
     463  997.34   483.3 1004.46   533.4 1029.48   543.4 1031.40   593.4 1057.19
   603.4 1059.18   643.4 1083.69   653.4 1093.88   683.4 1113.15   713.4 1125.77
   763.4 1134.19   813.4 1150.75   833.4 1153.51   863.4 1155.45   910.4 1149.57
#Mann= 3 , 0 , 0
       0     0.1       0     448   0.045       0     463     0.1       0
Bank Sta=     448,     463
Exp/Cntr=0.3,0.1

Type RM Length L Ch R = 1 ,266.2,260.3,266.2,272.1
XS GIS Cut Line= 3
     1707565.228      375936.023     1707150.937      376124.141
     1706736.647      376312.260
#Sta/Elev= 30
     1.1 1163.95   150.1 1136.66   193.4 1118.27   204.2 1111.92   215.0 1108.69
   236.6 1096.98   258.2 1087.68   290.6 1069.04   310.5 1054.70   323.1 1051.23
   334.3 1044.63   355.5 1030.99   366.3 1021.24   377.1 1016.55   393.5 1006.16
   447.5  996.62   452.7  996.20   462.5  996.59   517.6 1014.12   539.2 1022.62
   593.2 1037.51   614.8 1037.16   636.5 1033.43   690.5 1036.01   733.7 1032.25
   776.9 1033.13   810.3 1031.49   834.1 1027.45   885.0 1032.20   910.0 1032.20
#Mann= 3 , 0 , 0
       0     0.1       0   447.5   0.045       0   462.5     0.1       0
Bank Sta=   447.5,   462.5
Exp/Cntr=0.3,0.1